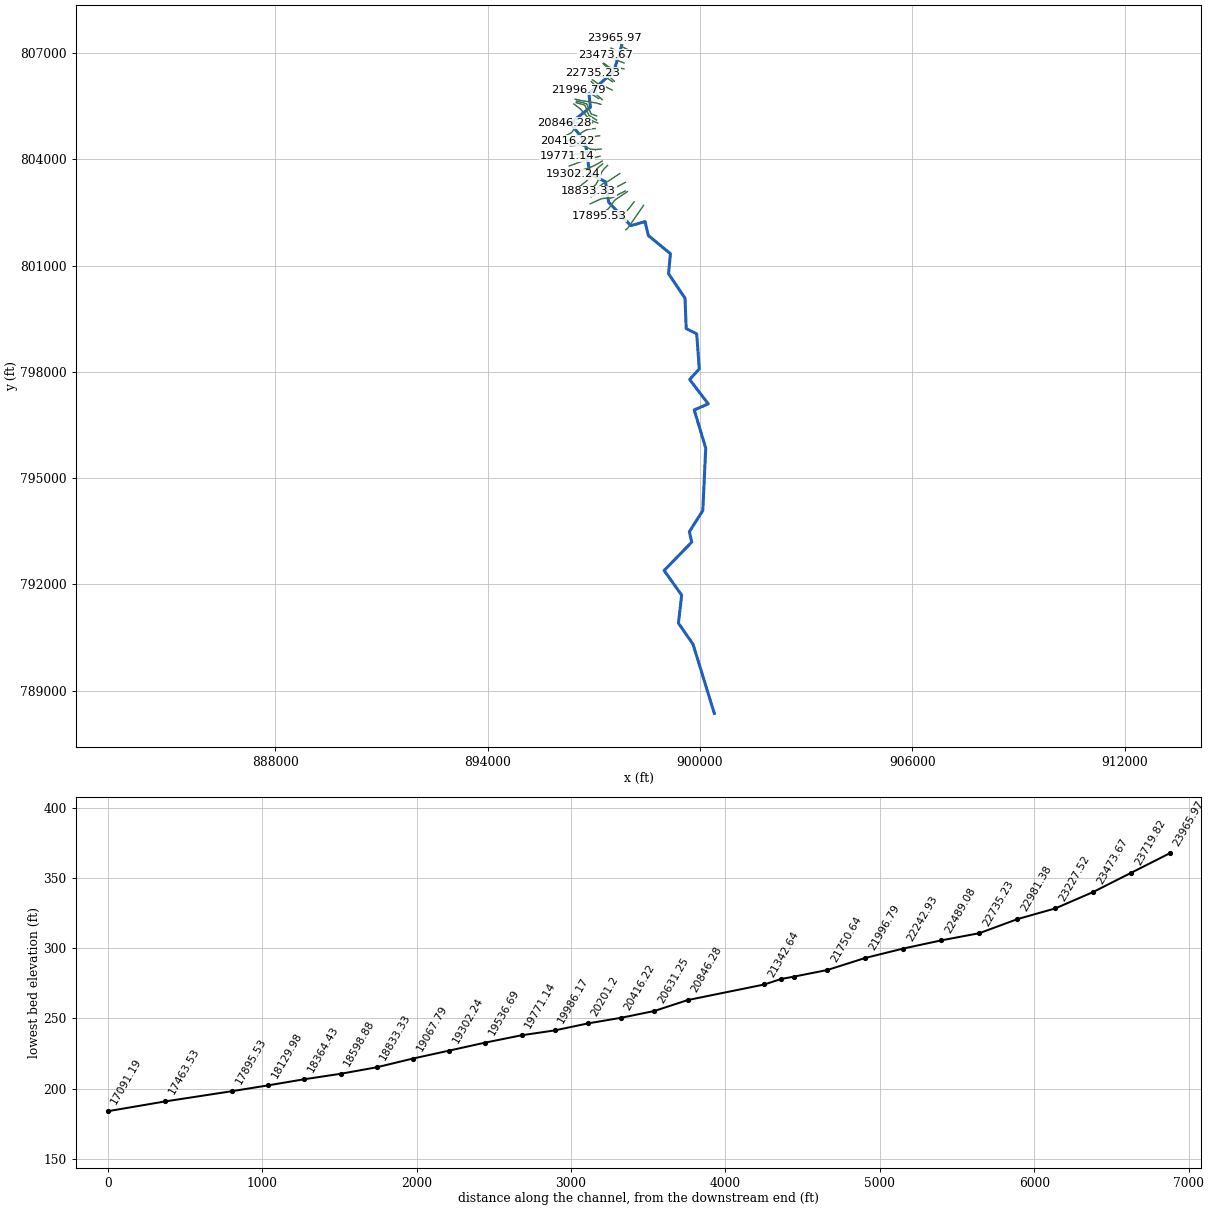
--- 11954_ras.prj (project) ---

Proj Title=11954
Current Plan=p01
Default Exp/Contr=0.3,0.1
English Units
Geom File=g01
Flow File=f01
Plan File=p01
Y Axis Title=Elevation
X Axis Title(PF)=Main Channel Distance
X Axis Title(XS)=Station
BEGIN DESCRIPTION:
RFD model 11954 exported to HEC-RAS
END DESCRIPTION:

--- 11954_ras.p01 (plan) ---

Plan Title=Plan 01
Program Version=4.10
Short Identifier=Plan 01
Geom File=g01
Flow File=f01
Subcritical Flow
Calc Critical at every XS
Secant Critical Depth

--- 11954_ras.f01 (steady flow) ---

Flow Title=Flow 01
Program Version=5.01
Number of Profiles= 6
Profile Names=10yr,25yr,50yr,100yr,100plus,500yr
River Rch & RM=11954,68,23965.97
  977.74 1364.52 1687.27 1920.05 2803.28 3289.57
River Rch & RM=11954,68,23719.82
  979.77 1367.61 1691.31 1924.87 2810.31 3297.48
River Rch & RM=11954,68,23473.67
  988.69  1381.2 1709.06 1946.03  2841.2  3332.2
River Rch & RM=11954,68,23227.52
 1049.79 1472.32 1826.57 2084.62 3043.55 3553.02
River Rch & RM=11954,68,22981.38
 1051.98 1475.76 1831.13 2090.13 3051.59 3562.23
River Rch & RM=11954,68,22735.23
 1059.21 1486.93 1845.84 2107.79 3077.38 3591.34
River Rch & RM=11954,68,22489.08
 1074.47 1510.27  1876.4  2144.3 3130.68 3650.79
River Rch & RM=11954,68,22242.93
 1082.04 1521.97  1891.8 2162.78 3157.67 3681.13
River Rch & RM=11954,68,21996.79
 1085.46 1527.24 1898.74  2171.1 3169.81 3694.76
River Rch & RM=11954,68,21750.64
  1088.5 1531.93  1904.9 2178.49  3180.6 3706.85
River Rch & RM=11954,68,21531.98
 1093.03 1538.92  1914.1 2189.54 3196.73 3724.96
River Rch & RM=11954,68,21450.94
 1094.17 1540.67 1916.41 2192.31 3200.77 3729.48
River Rch & RM=11954,68,21342.64
 1566.56 2214.85 2763.22 3167.89 4625.12 5138.78
River Rch & RM=11954,68,20846.28
 1577.59 2231.96 2785.82 3195.08 4664.82 5181.23
River Rch & RM=11954,68,20631.25
 1578.54 2233.48 2787.86 3197.55 4668.43  5185.2
River Rch & RM=11954,68,20416.22
 1593.04 2256.28 2818.21 3234.31 4722.09 5243.33
River Rch & RM=11954,68, 20201.2
 1599.68 2266.85 2832.39 3251.58 4747.31 5270.98
River Rch & RM=11954,68,19986.17
 1609.85 2283.02 2854.03 3277.92 4785.77 5313.01
River Rch & RM=11954,68,19771.14
 1622.07 2302.01 2879.14 3308.17 4829.93 5360.13
River Rch & RM=11954,68,19536.69
 1633.09 2319.55 2902.66 3336.81 4871.74  5405.8
River Rch & RM=11954,68,19302.24
 1641.24 2332.53 2920.06 3358.02 4902.71 5439.62
River Rch & RM=11954,68,19067.79
 1654.23  2353.3 2947.97 3392.09 4952.45 5494.08
River Rch & RM=11954,68,18833.33
 1656.88 2357.61 2953.81 3399.27 4962.94 5505.73
River Rch & RM=11954,68,18598.88
 1665.79 2372.04 2973.34 3423.25 4997.94 5544.47
River Rch & RM=11954,68,18364.43
  1887.5 2716.32 3428.88 3972.44 5799.76 6387.89
River Rch & RM=11954,68,18129.98
 1905.75 2745.68 3468.52 4021.05 5870.73 6464.56
River Rch & RM=11954,68,17895.53
 1913.92 2758.94 3486.51  4043.2 5903.07 6499.73
River Rch & RM=11954,68,17463.53
 1918.96 2767.13 3497.64  4056.9 5923.08 6521.52
River Rch & RM=11954,68,17091.19
 1923.95 2775.26  3508.7 4070.55 5943.01 6543.29
River Rch & RM=11954,68,16641.13
 2147.73 3945.52 4207.46    5476 6616.68 8161.41
River Rch & RM=11954,68,16284.11
 2153.37 3956.03 4218.54 5490.41 6634.09 8184.54
River Rch & RM=11954,68, 16058.6
  2160.3 3968.96 4232.18 5508.14 6655.52 8213.01
River Rch & RM=11954,68, 15833.1
 2165.93 3979.46 4243.25 5522.54 6672.91 8236.13
River Rch & RM=11954,68,15607.59
 2558.16 4711.99 5014.92  6525.8 7885.16 9858.17
River Rch & RM=11954,68,15382.08
 2559.42 4714.35 5017.41 6529.03 7889.06 9863.43
River Rch & RM=11954,68,15156.57
 2575.83 4745.04  5049.7 6571.02 7939.79 9931.75
River Rch & RM=11954,68,14931.06
 2582.55 4757.62 5062.94 6588.23 7960.59 9959.77
River Rch & RM=11954,68,14705.55
 2732.32 5037.83 5357.73 6971.44 8423.6310585.04
River Rch & RM=11954,68,14273.55
  2763.1 5095.45 5418.32 7050.21 8518.81 10713.9
River Rch & RM=11954,68,14035.48
 2780.55 5128.11 5452.67 7094.86 8572.7510786.98
River Rch & RM=11954,68,13797.41
 2787.19 5140.55 5465.74 7111.85 8593.2910814.81
River Rch & RM=11954,68,13559.34
 2796.31 5157.64 5483.71 7135.21 8621.5110853.07
River Rch & RM=11954,68,13321.26
 2817.87    5198 5526.14 7190.37 8688.1610943.45
River Rch & RM=11954,68,13083.19
 2828.63 5218.16 5547.34 7217.92 8721.4510988.62
River Rch & RM=11954,68,12845.12
 2836.08 5232.11    5562 7236.99 8744.4811019.88
River Rch & RM=11954,68,12607.05
 2838.56 5236.76 5566.89 7243.34 8752.1611030.29
River Rch & RM=11954,68,12368.98
 2907.92 5366.68 5703.46 7420.85 8966.6511321.69
River Rch & RM=11954,68, 12130.9
 2922.34 5393.69 5731.84 7457.75 9011.2311382.32
River Rch & RM=11954,68,11892.83
 2943.32 5433.01 5773.16 7511.45 9076.1211470.62
River Rch & RM=11954,68,11511.63
 2991.77 5523.82 5868.57 7635.47 9225.9811674.71
River Rch & RM=11954,68,11432.72
 2996.69 5533.04 5878.26 7648.06 9241.1911695.45
River Rch & RM=11954,68,11008.33
  3083.8 5696.34  6049.8 7871.03  9510.612063.05
River Rch & RM=11954,68,10571.65
 3186.72  5889.4 6252.52 8134.52 9828.98 12498.5
River Rch & RM=11954,68,10224.57
 3208.62 5930.48 6295.65 8190.58 9896.7212591.29
River Rch & RM=11954,68,9627.516
  3215.5 5943.41 6309.22 8208.21 9918.0212620.48
Boundary for River Rch & Prof#=11954,68,1
Up Type= 0
Dn Type= 2
Boundary for River Rch & Prof#=11954,68,2
Up Type= 0
Dn Type= 2
Boundary for River Rch & Prof#=11954,68,2
Up Type= 0
Dn Type= 2
Boundary for River Rch & Prof#=11954,68,2
Up Type= 0
Dn Type= 2
Boundary for River Rch & Prof#=11954,68,2
Up Type= 0
Dn Type= 2
Boundary for River Rch & Prof#=11954,68,2
Up Type= 0
Dn Type= 2

--- 11954_ras.g01 (geometry) ---

Geom Title=11954
Program Version=4.10

River Reach=11954,68
Reach XY= 30
897788.794688563807219.160553061897566.946334581806480.541009833
896863.859624463805869.198143845896906.190057043805471.262484746
896337.663182298805022.423920238896761.861729527804494.071606324
896887.793390629803581.451698023897332.901436137803372.913893303
897420.431330257802791.793349254898048.089406065 802128.61801407
 898449.64846362802244.679924067898541.312459638801852.143376518
 899165.35415452  801337.5280869899113.270821185800770.036767452
899578.200168452800079.042777768 899611.51734896799223.370100786
899908.190087785799070.432181574  899980.6614509 798083.46417926
899709.567187184797783.562623618900234.347210073797094.463850791
899837.211793408796925.193017448900163.496086456795844.837607445
900080.590651397794083.779808299899701.253069316793485.385729725
899766.904531415793190.600311415898988.378326584792390.212983221
899483.265174802791693.102918214899392.171616111790901.789862758
899804.053036173790308.427892652900405.046840091788354.553102876

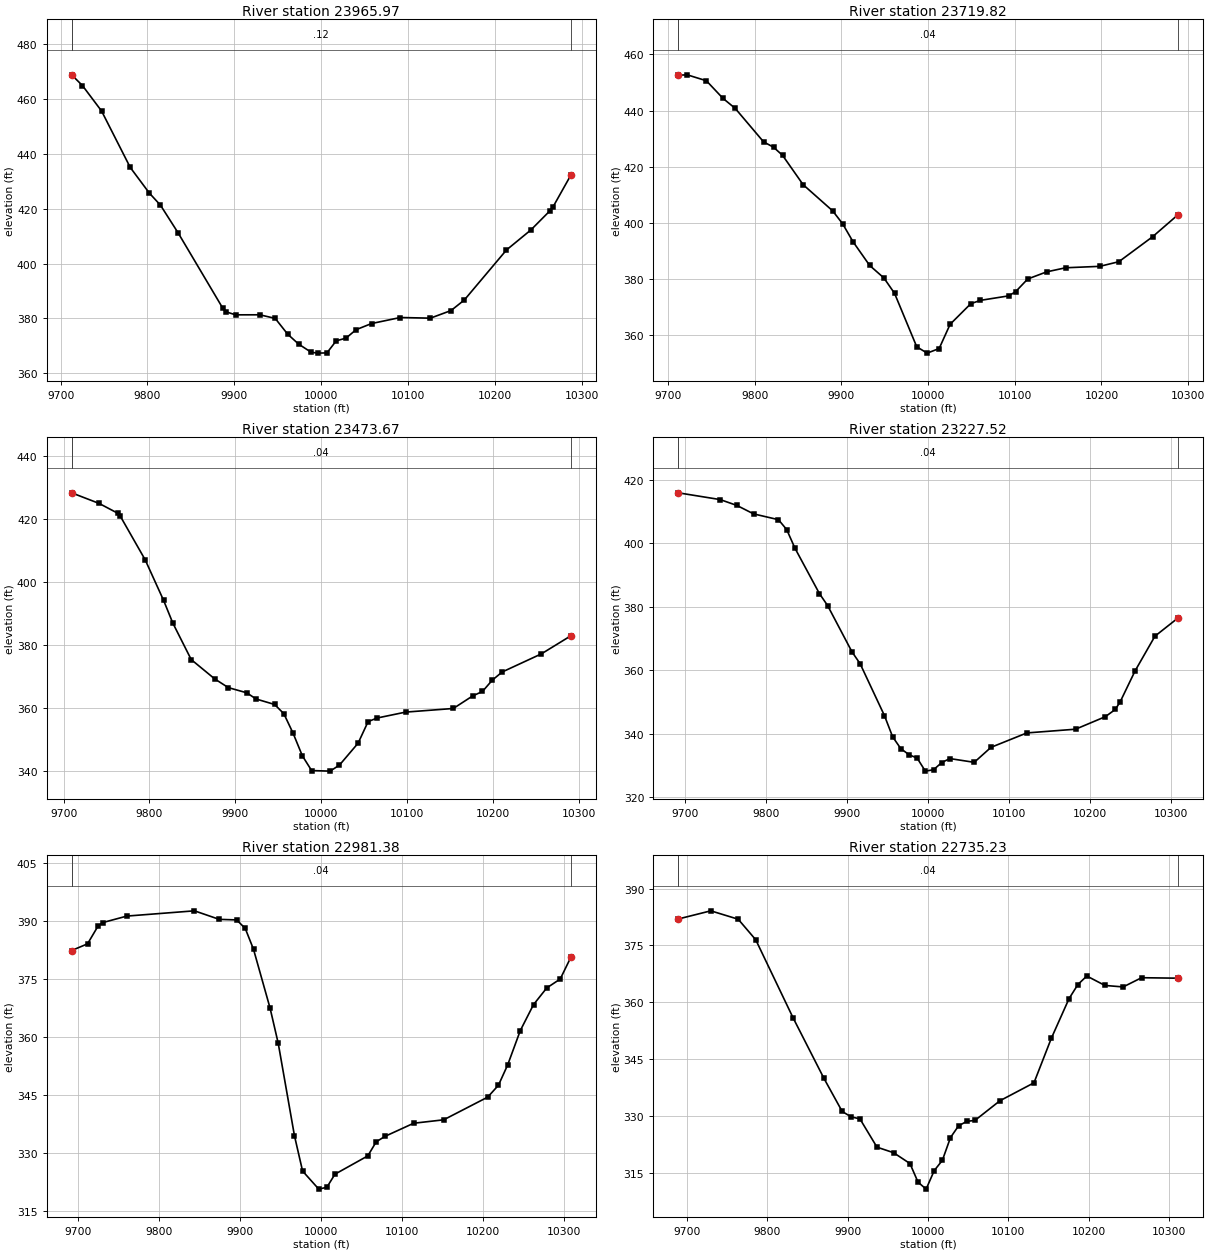
Type RM Length L Ch R = 1 ,23965.97,246.147300,246.147300,246.147300
XS GIS Cut Line= 6
898026.303722237807072.297699693897817.489259034807173.743682434
897798.258975069807194.961564921897774.112232102807250.107467074
897740.854800712807293.686906234897588.276103685807419.811987135
#Sta/Elev= 30
9712.698468.74199725.138464.83239747.148455.56559780.164435.00179802.174425.6505
9814.971 421.244 9835.19411.20439886.822383.64529890.215382.43659901.374 381.319
9929.231381.33629946.973380.0241 9961.29374.2925  9973.9370.66759988.332 367.699
9995.906367.373510006.51367.4644 10017.2371.846110028.44372.837810040.07375.9107
10057.86378.150910090.94 380.34510125.58380.109910149.34382.884910164.63 386.724
10213.14404.948510241.22412.239210262.79419.096410266.32420.423210287.31432.2641
#Mann= 3 , 0 , 0
9712.698    0.12       09712.698    0.12       010287.31    0.12       0
#XS Ineff= 2 , 0
       0                               0
Bank Sta=9712.698,10287.31
Exp/Cntr=0.3,0.1

Type RM Length L Ch R = 1 ,23719.82,246.147400,246.147400,246.147400
XS GIS Cut Line= 6
897994.211492783806873.042840177897828.794267033806955.756427683
 897779.70177047 806987.22352736897704.375614629807044.273833495
897580.958032744807099.053024112897489.329730283807145.823801589
#Sta/Elev= 30
 9712.07452.62269722.257452.75829744.374450.65179763.498 444.386 9777.55440.8421
9810.341428.90349821.876 426.9879832.231424.10849855.953413.66699890.029404.3443
9901.585399.72219913.463393.37349932.739384.90519949.097380.47429961.402 374.992
9986.978355.9748    9999353.715610012.82355.348710025.48363.979610049.26371.2865
10060.26372.487710093.08374.097410101.09375.609810114.97380.095610136.85382.6398
10158.73384.092910198.11384.600710220.11 386.25310259.09395.157710287.91402.8605
#Mann= 3 , 0 , 0
 9712.07    0.04       0 9712.07    0.04       010287.91    0.04       0
#XS Ineff= 2 , 0
       0                               0
Bank Sta=9712.07,10287.91
Exp/Cntr=0.3,0.1

Type RM Length L Ch R = 1 ,23473.67,246.147400,246.147400,246.147400
XS GIS Cut Line= 6
897854.808592094806724.503542364 897727.66222694806773.725328808
 897583.59701483806831.693663526897534.270574331806852.338576173
897433.169088357806901.414515886897324.914621673806961.365941823
#Sta/Elev= 30
9709.366 428.2569741.331424.89919762.777 421.828 9766.14420.79659794.947407.0401
9816.393394.17869827.116386.99179848.578375.39229875.871369.27889891.704366.5129
9913.267364.85439924.049 362.8999945.612361.16249956.393358.24239967.175352.0339
9977.956344.88289988.738340.207410010.32340.028410021.16341.948110042.84348.8879
10054.47355.713210064.78356.854110098.13358.7376 10153.7359.889710176.19363.8633
10187.62 365.28110199.06368.867110210.49371.445610256.21377.2037 10290.6382.9464
#Mann= 3 , 0 , 0
9709.366    0.04       09709.366    0.04       0 10290.6    0.04       0
#XS Ineff= 2 , 0
       0                               0
Bank Sta=9709.366,10290.6
Exp/Cntr=0.3,0.1

Type RM Length L Ch R = 1 ,23227.52,246.147300,246.147300,246.147300
XS GIS Cut Line= 6
897854.350542549806556.990151617897677.527053526806596.069630781
897517.411314679806585.562631726 897479.48293605806589.730027032
897418.659954205806619.700895924897282.088746532806715.802446722
#Sta/Elev= 30
9692.189415.87659743.666413.75529764.367411.90479784.963409.24629815.555407.4273
9825.729404.31549835.903398.46019866.124  384.159876.178380.40239906.206365.8413
9916.213362.12149946.267345.75849956.349339.0924 9966.43335.37319976.511333.4725
9986.592332.38959996.673328.297710006.74328.721210016.79330.975210026.85332.2505
10056.94331.066310077.57335.777510121.79 340.316 10181.9341.493210218.59 345.431
10230.82347.702210236.84350.092710255.27359.852910279.73370.763310307.74376.4072
#Mann= 3 , 0 , 0
9692.189    0.04       09692.189    0.04       010307.74    0.04       0
#XS Ineff= 2 , 0
       0                               0
Bank Sta=9692.189,10307.74
Exp/Cntr=0.3,0.1

Type RM Length L Ch R = 1 ,22981.38,246.147400,246.147400,246.147400
XS GIS Cut Line= 6
897580.028635153806210.038798232897499.549488408806284.880141157
897460.025298948806343.910754766 897438.72043944 806513.14337885
 897420.49812772806559.912046535897264.523146073 806703.28491467
#Sta/Elev= 30
9691.632382.37239711.289384.09949724.368388.7315 9730.36389.61359759.871391.2803
9843.347392.63789874.019390.43079895.498390.28479906.117388.07619916.342382.6627
9936.792367.4488 9946.87358.33589966.911 334.4389976.919325.32599996.929320.6507
10006.93321.134910016.93324.515710057.49329.249810067.89332.888410078.81334.3087
10114.11337.691710151.22338.578810205.67344.458210218.84347.517910230.27352.7795
10245.86361.6587 10262.2368.380910278.54372.688710295.17 374.99910308.41 380.667
#Mann= 3 , 0 , 0
9691.632    0.04       09691.632    0.04       010308.41    0.04       0
#XS Ineff= 2 , 0
       0                               0
Bank Sta=9691.632,10308.41
Exp/Cntr=0.3,0.1

Type RM Length L Ch R = 1 ,22735.23,246.147400,246.147400,246.147400
XS GIS Cut Line= 6
897532.945487491 806191.31711345897355.867091108 806311.25609623
897312.064176442806326.711680104897214.628589153806341.370174298
897146.771618566806360.833085129896976.585817741806447.913272206
#Sta/Elev= 30
 9689.32381.97519729.679384.12299763.762381.90799785.581376.48859832.093355.8685
 9870.47339.90089893.145  331.179904.405329.71179915.205329.21939936.479 321.731
9957.171320.26969977.504 317.4119987.571312.49969997.639310.654710007.73315.5497
10017.84318.251210027.95324.266810038.06327.371510048.17328.537310058.46328.8086
 10089.5333.987510131.86338.7234 10153.4350.449210175.46360.929810186.53364.6696
 10197.6366.915610220.11364.427710242.83364.029810265.79366.466310310.67366.3414
#Mann= 3 , 0 , 0
 9689.32    0.04       0 9689.32    0.04       010310.67    0.04       0
#XS Ineff= 2 , 0
       0                               0
Bank Sta=9689.32,10310.67
Exp/Cntr=0.3,0.1

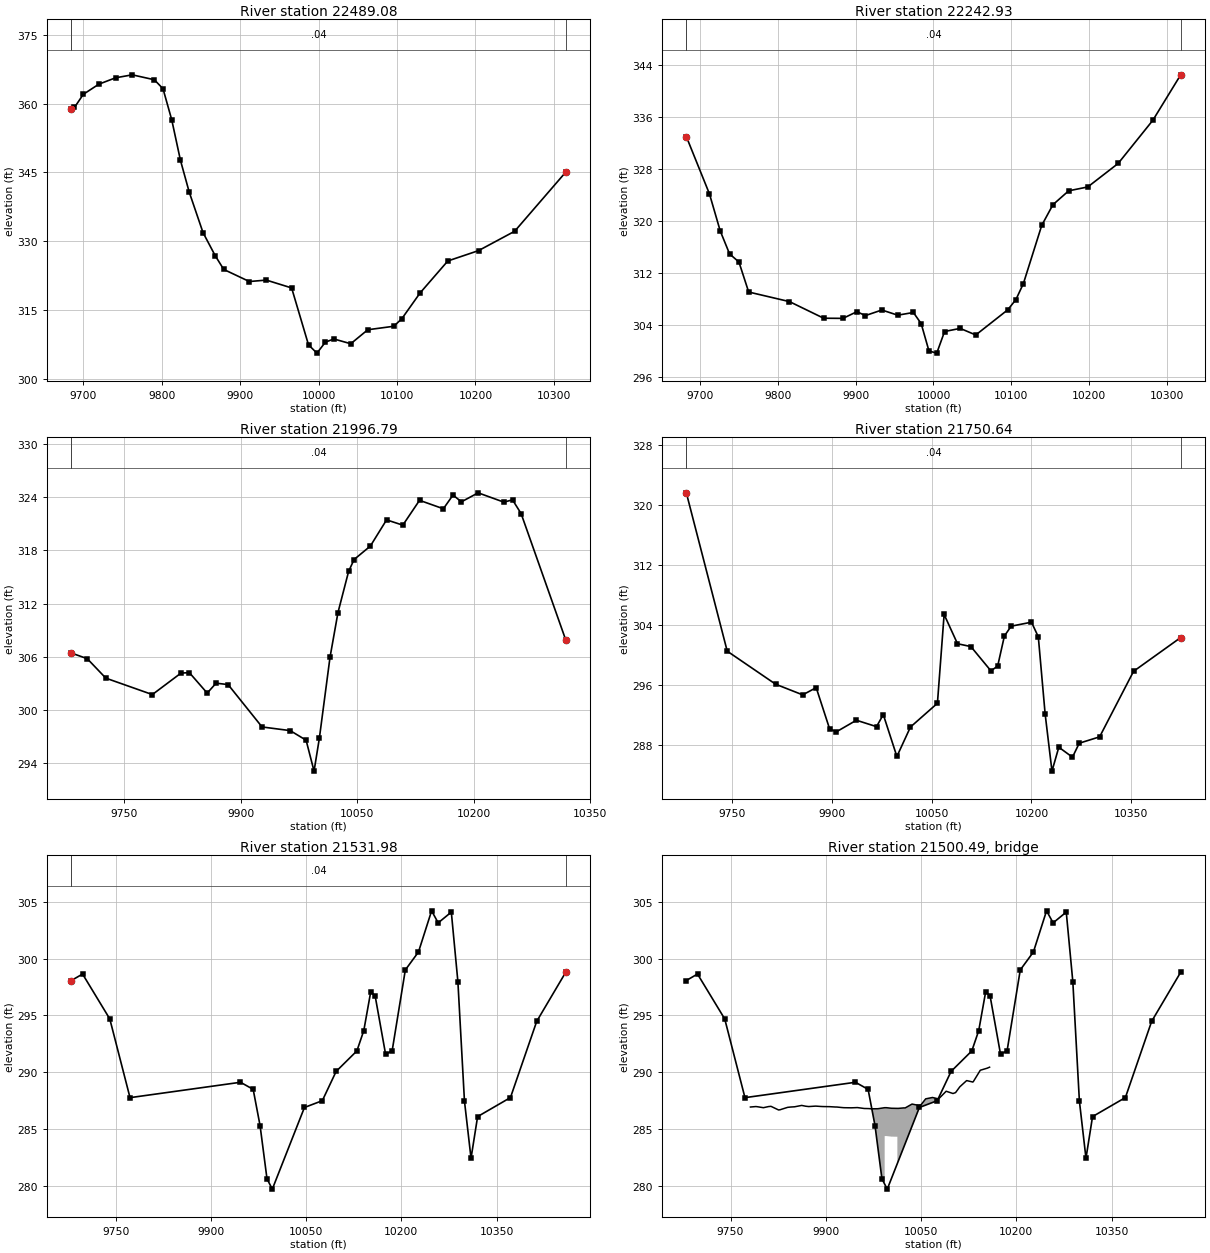
Type RM Length L Ch R = 1 ,22489.08,246.147400,246.147400,246.147400
XS GIS Cut Line= 6
897518.459105206805958.547238841897358.696568381806040.031528904
897182.099811772806112.174974069897135.695652166806133.720209386
897066.710501125806174.778391248896962.048559185806249.818089676
#Sta/Elev= 30
9684.783358.77149688.701359.18719700.028362.05879719.814364.26779741.106365.6575
9762.398366.30859790.495365.23569801.605363.27939812.715356.51029823.825347.6734
9834.935340.7649 9852.61331.87819868.184326.81889879.074323.82069911.745321.1795
9933.378321.4928 9965.64319.78069987.148307.35689997.902 305.547 10008.7307.9439
10019.48308.641210041.03307.596110062.77310.652910095.84311.4105 10106.1313.0476
10129.45318.6887 10164.8325.667410203.96 327.92710250.04332.1548 10315.2345.0704
#Mann= 3 , 0 , 0
9684.783    0.04       09684.783    0.04       0 10315.2    0.04       0
#XS Ineff= 2 , 0
       0                               0
Bank Sta=9684.783,10315.2
Exp/Cntr=0.3,0.1

Type RM Length L Ch R = 1 ,22242.93,246.147300,246.147300,246.147300
XS GIS Cut Line= 6
897241.217379573805688.529474553897090.171621849805818.844195451
897068.778253945805876.142802323 897052.34818499806044.056294117
897004.208815105806123.746648667896929.343437682806202.287083504
#Sta/Elev= 30
9682.723332.98339712.447324.17299726.231   318.59738.244314.96959750.257313.7238
 9762.77 309.1189815.164307.64449859.007305.09649883.781305.07239901.812306.1062
9912.432 305.4949933.673306.35679954.117305.56349974.191305.97669984.196304.2665
9994.202300.062910004.21299.737310014.23303.055810034.25 303.53510054.27302.5242
10095.27 306.38110105.84307.964910115.41310.418810138.97319.357510153.31322.5217
10173.54324.654210198.03325.247310237.04328.854110281.62335.491110317.33342.4607
#Mann= 3 , 0 , 0
9682.723    0.04       09682.723    0.04       010317.33    0.04       0
#XS Ineff= 2 , 0
       0                               0
Bank Sta=9682.723,10317.33
Exp/Cntr=0.3,0.1

Type RM Length L Ch R = 1 ,21996.79,246.147400,246.147400,246.147400
XS GIS Cut Line= 6
897142.030643698805717.150560706896971.528492101805824.990357325
896930.404341602805840.025945116896825.454115605805863.860214761
 896754.26848929805885.738317411896563.115890041 805970.35568145
#Sta/Elev= 30
9681.581306.39789701.989305.76139725.955303.55919785.871301.7021 9822.87304.1364
9833.636304.17479856.546301.86819868.001302.9908 9883.46302.83189927.219298.0396
9963.475297.62649983.956296.54289994.196293.0446   10001 296.73610014.73305.8987
10025.02310.978910038.73315.632410045.79316.975710066.71318.492310087.63321.4583
10108.56320.8611 10130.1323.669410160.79322.712610173.23324.268910184.02323.4954
10205.58324.515910238.78 323.46210249.86323.724510260.95322.169810318.47307.8718
#Mann= 3 , 0 , 0
9681.581    0.04       09681.581    0.04       010318.47    0.04       0
#XS Ineff= 2 , 0
       0                10131.23       0
Bank Sta=9681.581,10318.47
Exp/Cntr=0.3,0.1

Type RM Length L Ch R = 1 ,21750.64,218.662200,218.662200,218.662200
XS GIS Cut Line= 6
897203.085245195805553.548462448897072.788499061805594.658621663
896926.318994945805616.723659329896851.920157176805632.188871086
896710.852597466805650.621592715896475.593741661805702.284102845
#Sta/Elev= 30
9680.624321.58699742.185300.45729815.059296.0473 9855.77294.62799876.084295.5909
9896.254290.09819906.339289.68989936.593291.24229966.866290.38769977.087291.9929
9997.528286.403910017.96290.335210058.55 293.50510068.62305.354310088.76301.4506
 10108.9 301.07110139.11297.827510149.23 298.47610159.35302.480410169.48 303.791
 10200.1 304.32610210.39302.368710220.67 292.07110230.96284.450510241.24287.6432
10261.79286.310410272.01288.176410302.66289.024510353.76297.771710424.69302.2748
#Mann= 3 , 0 , 0
9680.624    0.04       09680.624    0.04       010424.69    0.04       0
#XS Ineff= 2 , 0
       0                10165.83       0
Bank Sta=9680.624,10424.69
Exp/Cntr=0.3,0.1

Type RM Length L Ch R = 1 ,21531.98,81.033000,81.033000,81.033000
XS GIS Cut Line= 5
897081.968593717805229.085681155 896926.17234084805284.628813401
896879.100260943805389.952592015896800.975260943805571.376203135
896510.827691525805648.416133672
#Sta/Elev= 30
9680.382298.07899697.994298.65039740.863294.69259772.712287.75479946.688289.1103
9966.643288.4865 9977.53285.28469988.418280.59879996.798 279.69310047.37286.8888
10075.52287.4876 10097.3290.069210129.96291.874610140.85 293.66810151.73297.0744
10158.68296.733710175.21291.568710185.55291.902810206.25299.011510226.94 300.594
10247.63304.220510257.98303.160710278.67304.107510289.02297.974110299.36287.4531
10309.71 282.41710320.06286.084110371.79287.763110413.18294.484210458.88298.8118
#Mann= 3 , 0 , 0
9680.382    0.04       09680.382    0.04       010458.88    0.04       0
#XS Ineff= 2 , 0
       0                10234.84       0
Bank Sta=9680.382,10458.88
Exp/Cntr=0.3,0.1

Type RM Length L Ch R = 3 ,21500.49,,,
BEGIN DESCRIPTION:
END DESCRIPTION:
Bridge Culvert--1,0,-1,-1, 0
Deck Dist Width WeirC Skew NumUp NumDn MinLoCord MaxHiCord MaxSubmerge Is_Ogee
28.706500,23.620000,2.6,0, 57, 57, , , 0.95, 0, 0,0,,
 9781.33 9789.77 9791.72 9801.73 9809.97 9813.68 9825.64 9828.22 9829.76 9839.89
 9845.05 9850.96 9862.03 9868.39 9873.09 9884.16 9891.72 9895.23 9906.30 9915.06
 9917.36 9924.11 9928.31 9939.06 9940.80 9949.81 9960.56 9968.06 9971.31 9982.06
 9992.72 9992.72 9992.80 9995.3110003.5510012.7310012.7310014.3010022.5710025.05
10035.8010046.5510049.8310057.3010068.0510077.0910078.8010089.5510100.3010104.35
10111.0510121.8010131.6010132.5510143.3010154.0510157.91
  286.93  286.97  286.96  286.87  286.97  286.99  286.67  286.69  286.72  286.90
  286.93  286.95  287.07  287.00  286.97  287.01  286.98  286.97  286.96  286.93
  286.93  286.89  286.87  286.86  286.86  286.88  286.80  286.79  286.77  286.78
  286.87  286.87  286.87  286.87  286.82  286.81  286.81  286.81  286.85  286.85
  287.19  287.07  287.12  287.65  287.77  287.65  287.71  288.32  288.12  288.20
  288.71  289.26  289.13  289.19  290.17  290.35  290.44
 -713.07 -713.03 -713.04 -713.13 -713.03 -713.01 -713.33 -713.31 -713.28 -713.10
 -713.07 -713.05 -712.93 -713.00 -713.03 -712.99 -713.02 -713.03 -713.04 -713.07
 -713.07 -713.11 -713.13 -713.14 -713.14 -713.12 -713.20 -713.21 -713.23 -713.22
 -713.13  284.37  284.37  284.37  284.32  284.31 -713.19 -713.19 -713.15 -713.15
 -712.81 -712.93 -712.88 -712.35 -712.23 -712.35 -712.29 -711.68 -711.88 -711.80
 -711.29 -710.74 -710.87 -710.81 -709.83 -709.65 -709.56
 9781.33 9789.77 9791.72 9801.73 9809.97 9813.68 9825.64 9828.22 9829.76 9839.89
 9845.05 9850.96 9862.03 9868.39 9873.09 9884.16 9891.72 9895.23 9906.30 9915.06
 9917.36 9924.11 9928.31 9939.06 9940.80 9949.81 9960.56 9968.06 9971.31 9982.06
 9985.67 9985.67 9992.80 9995.3110003.5510005.6810005.6810014.3010022.5710025.05
10035.8010046.5510049.8310057.3010068.0510077.0910078.8010089.5510100.3010104.35
10111.0510121.8010131.6010132.5510143.3010154.0510157.91
  286.93  286.97  286.96  286.87  286.97  286.99  286.67  286.69  286.72  286.90
  286.93  286.95  287.07  287.00  286.97  287.01  286.98  286.97  286.96  286.93
  286.93  286.89  286.87  286.86  286.86  286.88  286.80  286.79  286.77  286.78
  286.81  286.81  286.87  286.87  286.82  286.82  286.82  286.81  286.85  286.85
  287.19  287.07  287.12  287.65  287.77  287.65  287.71  288.32  288.12  288.20
  288.71  289.26  289.13  289.19  290.17  290.35  290.44
 -713.07 -713.03 -713.04 -713.13 -713.03 -713.01 -713.33 -713.31 -713.28 -713.10
 -713.07 -713.05 -712.93 -713.00 -713.03 -712.99 -713.02 -713.03 -713.04 -713.07
 -713.07 -713.11 -713.13 -713.14 -713.14 -713.12 -713.20 -713.21 -713.23 -713.22
 -713.19  284.31  284.37  284.37  284.32  284.32 -713.18 -713.19 -713.15 -713.15
 -712.81 -712.93 -712.88 -712.35 -712.23 -712.35 -712.29 -711.68 -711.88 -711.80
 -711.29 -710.74 -710.87 -710.81 -709.83 -709.65 -709.56
BR Coef=-1 , 0 , 0 ,, 0 ,,,0.8,0,1,0,
WSPro=,,,, 1 ,,,, 0 ,,,, 0 ,,,,-1 ,-1 ,-1 , 0 , 0 , 0 , 0 , 0
BC Design=,, 0 ,, 0 ,,,,,,

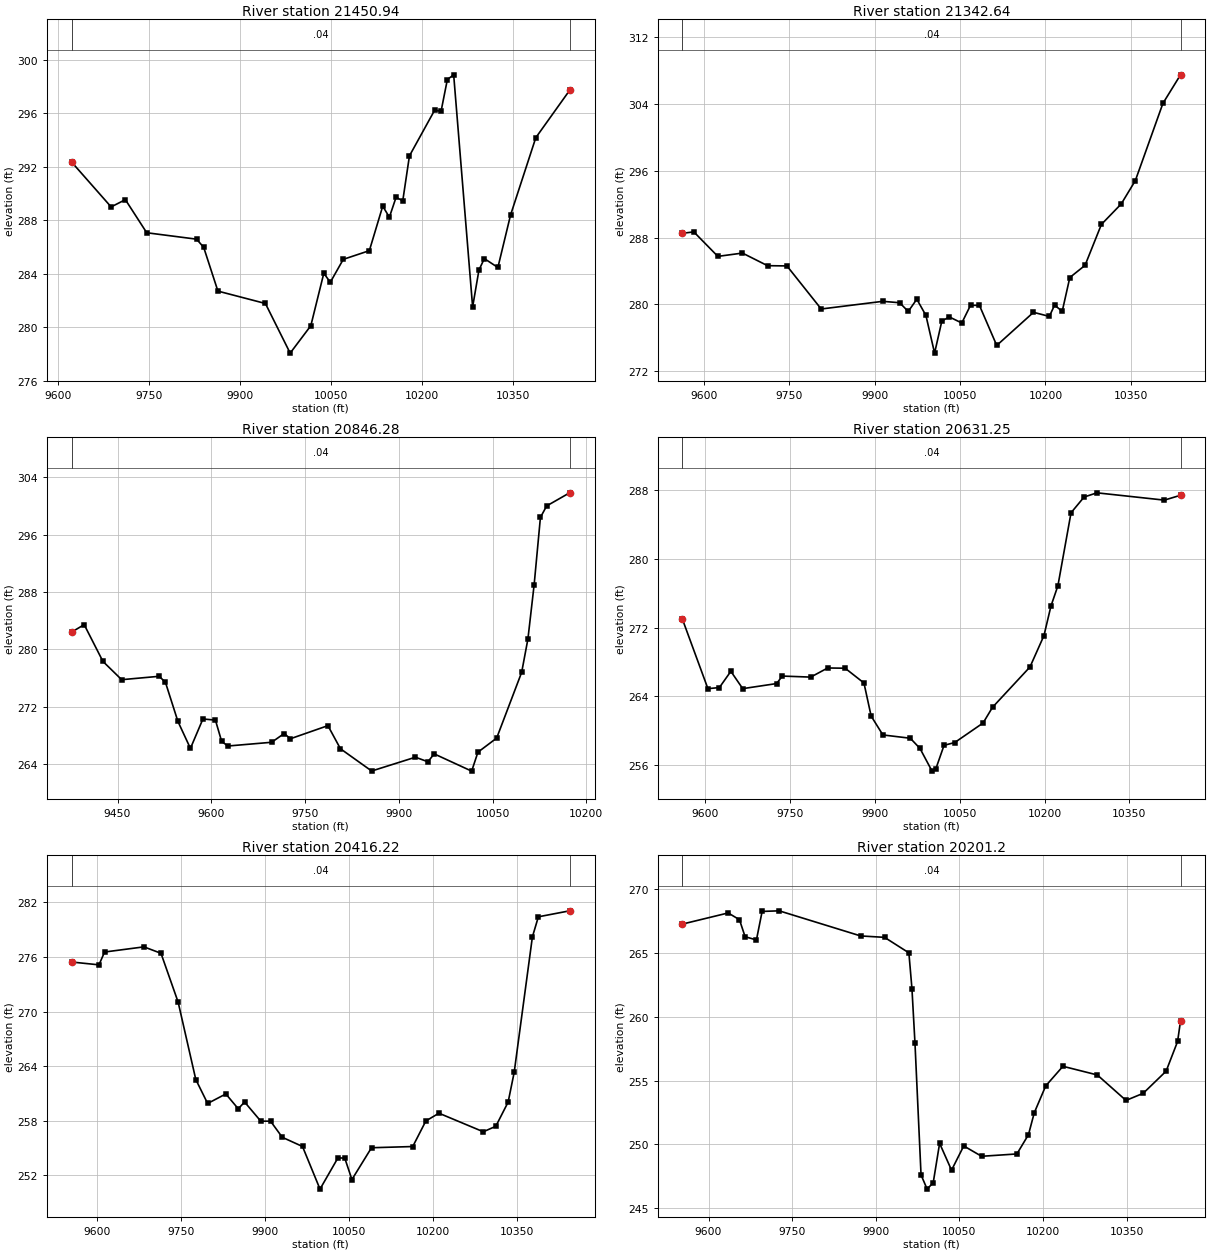
Type RM Length L Ch R = 1 ,21450.94,108.304800,108.304800,108.304800
XS GIS Cut Line= 5
897080.571715832805111.747940764896861.971492618805246.118539736
896780.714089662805459.419222504896746.706109643805532.845543087
896501.496094316805604.362314224
#Sta/Elev= 30
9621.979292.3469 9687.21 288.9889710.686289.53159745.901287.05639828.068286.5757
9839.806285.96819863.282282.69179941.585281.76499982.429278.052510016.49280.1041
10037.89284.0281 10048.6283.3508   10070285.066610112.98285.716310135.02289.0409
10146.04288.219810157.06289.710210168.08289.4429 10179.1292.806310220.78296.2327
10231.19296.131510241.61298.515710252.03298.867810283.28281.507810293.69284.2651
10302.59 285.12310324.94284.458210345.78288.375610387.44294.166310443.18297.7061
#Mann= 3 , 0 , 0
9621.979    0.04       09621.979    0.04       010443.18    0.04       0
#XS Ineff= 2 , 0
       0                10209.08       0
Bank Sta=9621.979,10443.18
Exp/Cntr=0.3,0.1

Type RM Length L Ch R = 1 ,21342.64,496.362800,496.362800,496.362800
XS GIS Cut Line= 6
897113.812495848805029.906838266 896985.16218369805078.733026624
  896888.9633953805137.863337236896810.767987467805210.285267654
896616.042989941805430.668268359896439.269774327805565.071415957
#Sta/Elev= 30
9562.982288.50519582.843288.67989625.071285.74389668.212286.14049712.244284.6321
9746.335284.60119806.458 279.4469914.466280.3625 9944.16280.19439959.204279.1512
9974.248280.61579990.237 278.67810005.44274.1626 10018.2278.012110031.39278.4935
10053.18277.769210068.52279.888610084.14279.880810114.53275.081510179.05279.0472
10206.83 278.55810216.09279.907910229.45279.1636 10242.8 283.21410269.52284.6721
10298.23289.571110333.02292.021810357.79294.815810406.14 304.05410437.08307.4783
#Mann= 3 , 0 , 0
9562.982    0.04       09562.982    0.04       010437.08    0.04       0
#XS Ineff= 2 , 0
       0                               0
Bank Sta=9562.982,10437.08
Exp/Cntr=0.3,0.1

Type RM Length L Ch R = 1 ,20846.28,215.027000,215.027000,215.027000
XS GIS Cut Line= 2
896965.177074994805035.617436178896168.302074994805030.409102845
#Sta/Elev= 30
9376.462282.4142 9396.64283.4587 9426.64278.33949456.641275.79419516.642276.2661
9526.642275.43199546.643269.98069566.643266.22789586.644270.32729606.644270.1654
9616.644267.18979626.644266.56179696.646267.08089716.646268.30089726.647267.5726
9786.648269.39639806.648266.18189856.649263.07979926.651265.00249946.651264.3661
9956.651265.467210016.65 263.06410026.65265.699110056.65267.663710096.65276.8208
10106.65281.462710116.65289.044810126.66298.387810136.66299.985210173.35301.8093
#Mann= 3 , 0 , 0
9376.462    0.04       09376.462    0.04       010173.35    0.04       0
#XS Ineff= 2 , 0
       0                               0
Bank Sta=9376.462,10173.35
Exp/Cntr=0.3,0.1

Type RM Length L Ch R = 1 ,20631.25,215.027100,215.027100,215.027100
XS GIS Cut Line= 6
896859.357991115804967.310776019896647.567733372804998.915289948
896563.587877659 804987.85167393 896516.19211059804950.522776007
896373.679481857804755.561133944896128.135535608804630.783437597
#Sta/Elev= 30
9559.638272.9499 9604.62264.90399624.902265.03189645.183266.91689666.174264.9061
9726.106265.4948 9736.17266.36579786.412266.24529816.445267.30579847.285267.2768
 9880.55265.56369893.288261.71799914.056 259.5299962.525259.14579979.594257.9666
   10001 255.327 10007.8255.6145 10022.2 258.32410041.01258.6444 10091.2260.9151
10107.93262.741710174.16267.421610198.86271.061210211.22274.486210223.57276.8578
10246.77285.327310269.85287.155610292.59287.644310411.81286.796410440.38287.3602
#Mann= 3 , 0 , 0
9559.638    0.04       09559.638    0.04       010440.38    0.04       0
#XS Ineff= 2 , 0
       0                               0
Bank Sta=9559.638,10440.38
Exp/Cntr=0.3,0.1

Type RM Length L Ch R = 1 ,20416.22,215.027000,215.027000,215.027000
XS GIS Cut Line= 6
897043.913005229804872.079007601896900.466731462804862.908599352
896791.279411422804832.201347628896696.968491745804781.420825362
896434.047071207804606.524423148896242.624432595804523.645881399
#Sta/Elev= 30
9555.325275.44849604.257275.1367 9614.26276.54529684.563277.11229714.996276.4076
9745.661271.03619777.178262.53649798.314259.90429830.843260.95069852.992259.3187
9864.303260.06589893.246257.9604 9910.71257.95649931.625256.18749967.747255.1778
    9999250.491710031.03253.926310043.22253.901210055.99251.545410090.96255.0392
10164.63255.171710188.02257.981510211.41258.833810290.63256.795310312.93257.3965
10334.96260.054510345.79263.329110378.29278.205710388.95280.414810444.74281.0724
#Mann= 3 , 0 , 0
9555.325    0.04       09555.325    0.04       010444.74    0.04       0
#XS Ineff= 2 , 0
       0                               0
Bank Sta=9555.325,10444.74
Exp/Cntr=0.3,0.1

Type RM Length L Ch R = 1 , 20201.2,215.027100,215.027100,215.027100
XS GIS Cut Line= 6
897166.259404732804668.796505162897046.195535041804652.050216817
896926.474838958804623.967082702896825.224873036804589.105698911
896619.105843771804502.836840099896309.885689809804426.307795684
#Sta/Elev= 30
9553.251267.2814 9635.22268.15279655.466267.62419665.588266.2877 9685.93266.0353
9696.138268.27289726.762268.31939872.884266.34939915.782266.23879959.423265.0234
9964.909262.22569970.333257.96089981.244247.60389992.154246.486310003.09246.9935
10014.56250.079910035.95247.972410057.86 249.87510089.91249.0623 10153.2249.2463
10173.97250.758110184.36252.473710204.95254.586410235.81256.122710297.51255.4429
10348.93253.446410379.78254.002310420.92255.742110441.49 258.06910446.75259.6762
#Mann= 3 , 0 , 0
9553.251    0.04       09553.251    0.04       010446.75    0.04       0
#XS Ineff= 2 , 0
       0                               0
Bank Sta=9553.251,10446.75
Exp/Cntr=0.3,0.1

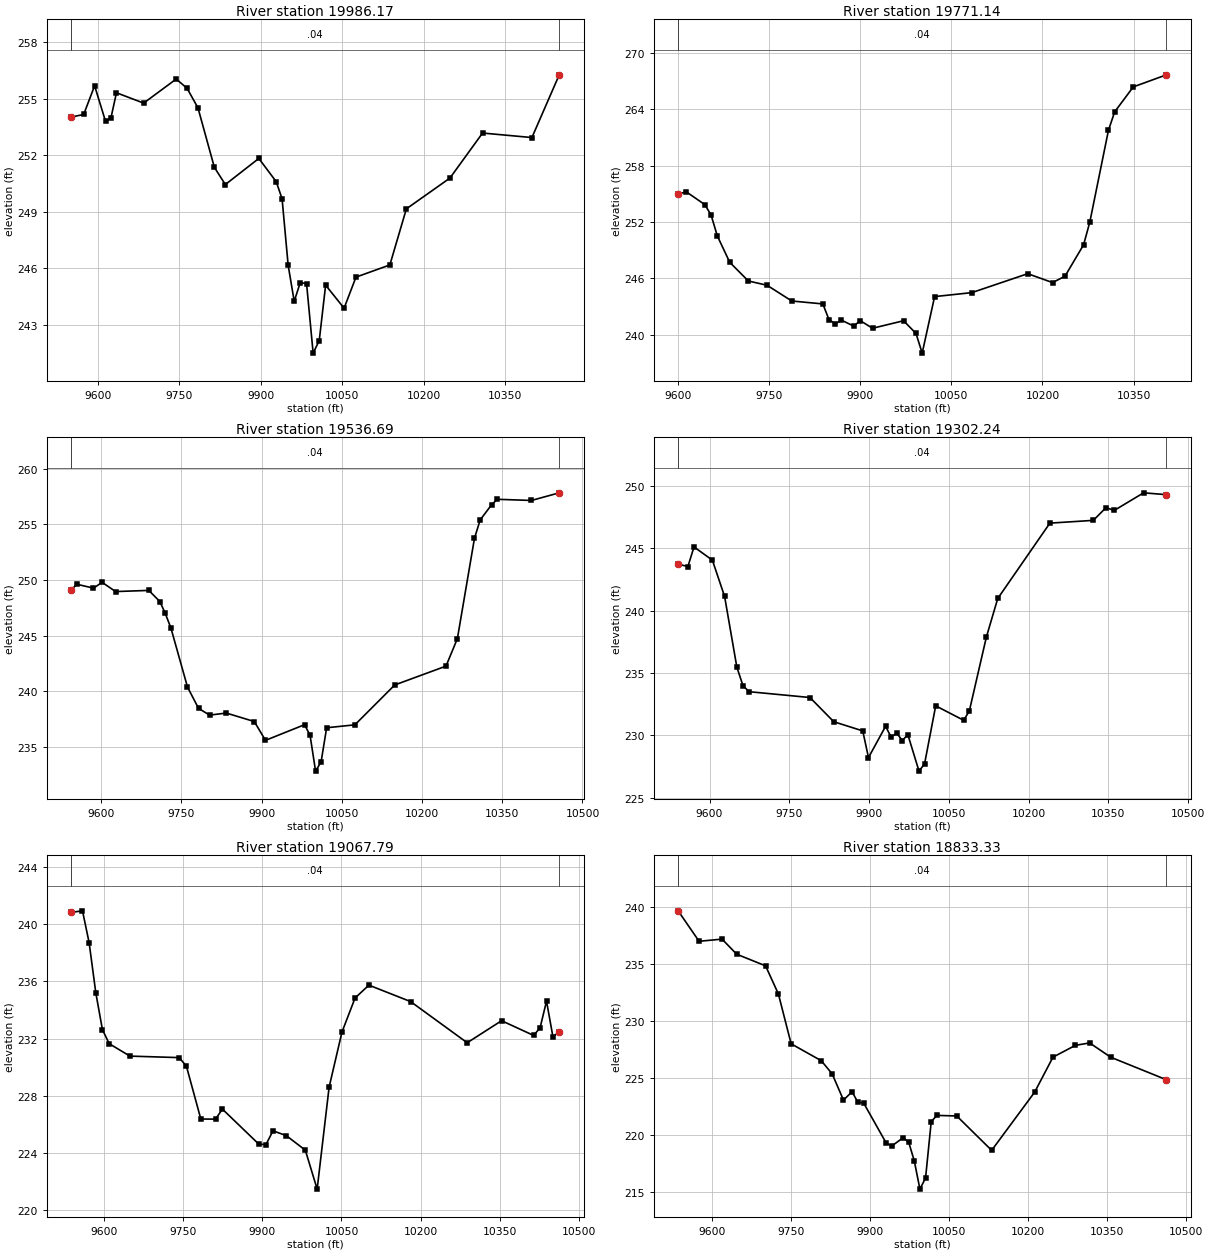
Type RM Length L Ch R = 1 ,19986.17,215.027000,215.027000,215.027000
XS GIS Cut Line= 6
897208.344249743 804291.92260087897052.920788407804279.581715963
896911.069028802804290.905322704896700.741813845804383.524232966
896602.665183147804405.433120627896335.522253908804383.339759127
#Sta/Elev= 30
9550.291254.03249573.761254.17359593.868255.69719613.976253.8069 9624.03254.0001
9634.084255.32549684.176254.77569744.211256.05419764.219255.55889784.254254.5219
9814.421251.36669834.675250.45449896.333251.8388 9928.33250.6085 9939.17249.6998
9950.339246.17359961.507244.25769972.675245.25069984.298245.19099996.379241.5059
10007.65242.175910019.36245.113510053.39 243.89110075.27245.5398 10137.7246.1864
 10168.1 249.16410248.36250.797810308.46253.187510399.36252.947210449.67256.2768
#Mann= 3 , 0 , 0
9550.291    0.04       09550.291    0.04       010449.67    0.04       0
#XS Ineff= 2 , 0
       0                               0
Bank Sta=9550.291,10449.67
Exp/Cntr=0.3,0.1

Type RM Length L Ch R = 1 ,19771.14,234.452000,234.452000,234.452000
XS GIS Cut Line= 2
897038.093741661804264.784102845896251.635408328804098.117436178
#Sta/Elev= 30
9600.097254.97049613.481255.21669644.148253.8445 9654.37 252.7379664.592 250.524
9685.036247.71329715.702245.72139746.368 245.2719787.257243.59019838.367243.2805
9848.589241.58649858.811241.17549869.033 241.5469889.478240.9163  9899.7241.5101
9920.144240.68869971.254241.48879991.698240.140810001.92238.042910022.36244.0597
 10083.7244.4839 10175.7246.497410216.58245.552310237.03246.229510267.69249.5783
10277.92     25210308.58261.757110318.81263.722810349.47266.380910404.02267.6656
#Mann= 3 , 0 , 0
9600.097    0.04       09600.097    0.04       010404.02    0.04       0
#XS Ineff= 2 , 0
       0                               0
Bank Sta=9600.097,10404.02
Exp/Cntr=0.3,0.1

Type RM Length L Ch R = 1 ,19536.69,234.452100,234.452100,234.452100
XS GIS Cut Line= 6
897175.769668943804089.831061764 896915.27746864804021.317344951
896763.711811008803974.861196749896734.903959369803967.756717639
896699.411461327803958.287021309896306.171947256  803814.1783436
#Sta/Elev= 30
9543.451249.10189554.587249.61829585.607249.27379601.757249.79159626.967248.9649
9689.008249.06859709.688248.07119719.697247.01889730.368245.69429761.389240.3923
9782.069238.47939802.749237.87619834.011238.05999886.307237.29989907.225235.6113
9980.306237.01649990.612  236.06 10000.9232.848610011.25233.6871 10021.6236.7413
10074.38237.003410148.94 240.58210244.79242.273110266.09244.744310298.04253.7466
10308.69255.394710329.99256.751310340.64257.246110404.54257.141510456.55257.8267
#Mann= 3 , 0 , 0
9543.451    0.04       09543.451    0.04       010456.55    0.04       0
#XS Ineff= 2 , 0
       0                               0
Bank Sta=9543.451,10456.55
Exp/Cntr=0.3,0.1

Type RM Length L Ch R = 1 ,19302.24,234.452000,234.452000,234.452000
XS GIS Cut Line= 6
897240.966212115803953.092173403897058.262349393803849.242591839
896961.959089768803800.547781227896898.649050286 803775.47551857
896692.778033213803707.001430779896406.118073268803577.128514219
#Sta/Elev= 30
9541.024243.72649559.389243.53979570.892245.10749605.399244.04859628.405241.1388
 9651.41235.47519662.912233.98999674.415233.50579788.823233.03979833.621 231.098
9888.117230.36339898.872228.22329931.035230.72999941.507229.86459951.978230.1836
 9962.45229.59219972.921230.06149993.864227.138710004.32 227.72210025.24232.3731
10077.89231.213110088.55231.972510120.55237.889810141.89240.975510239.91247.0164
10321.64247.238310345.38248.255910360.98248.036810416.11249.445510458.99249.2991
#Mann= 3 , 0 , 0
9541.024    0.04       09541.024    0.04       010458.99    0.04       0
#XS Ineff= 2 , 0
       0                               0
Bank Sta=9541.024,10458.99
Exp/Cntr=0.3,0.1

Type RM Length L Ch R = 1 ,19067.79,234.452100,234.452100,234.452100
XS GIS Cut Line= 6
897252.386413451803873.150367495897126.667586445803771.064193445
897002.422545613803651.159890475896889.476489492803489.527510253
896808.893640926803400.678498373896595.243171524803231.282582483
#Sta/Elev= 30
9537.149 240.8269559.021240.93639571.601238.70989584.181235.22469596.761232.6377
9609.701231.64979648.969230.78339742.383230.67829756.037230.07799783.346 226.386
9811.329226.37999824.228227.08029893.452224.62559906.822224.60339920.185225.5613
9945.391225.22699981.474 224.20910003.88221.487210026.56228.613410050.95232.4665
10075.76234.843110101.96235.742810181.11234.592910288.35231.717110353.53233.2567
10414.34232.226510426.54 232.76610438.73234.625810450.93232.120110462.83232.4966
#Mann= 3 , 0 , 0
9537.149    0.04       09537.149    0.04       010462.83    0.04       0
#XS Ineff= 2 , 0
       0                               0
Bank Sta=9537.149,10462.83
Exp/Cntr=0.3,0.1

Type RM Length L Ch R = 1 ,18833.33,234.452000,234.452000,234.452000
XS GIS Cut Line= 6
897391.880728572803831.399241178897296.130379478803739.499670994
897221.704851461803639.212824719897106.121940484 803369.66339762
897054.332056612803285.081118018896852.259548105803097.668893338
#Sta/Elev= 30
9536.364239.64229576.169236.97539619.754237.16469647.598 235.8439702.439234.8242
9726.773232.36189750.944227.99949808.125226.5183  9828.9225.36549850.344223.0679
9866.687223.80369877.705222.87389888.566222.81979931.345219.3213 9942.04219.0472
9963.429219.76939974.124219.39279984.819217.74899995.514 215.27310006.25216.2515
10016.99221.180410027.72221.729410065.49221.678210131.76218.667710213.43223.7666
 10248.2226.828710290.87227.864510317.87228.074510357.76226.825410463.63224.8511
#Mann= 3 , 0 , 0
9536.364    0.04       09536.364    0.04       010463.63    0.04       0
#XS Ineff= 2 , 0
       0                               0
Bank Sta=9536.364,10463.63
Exp/Cntr=0.3,0.1

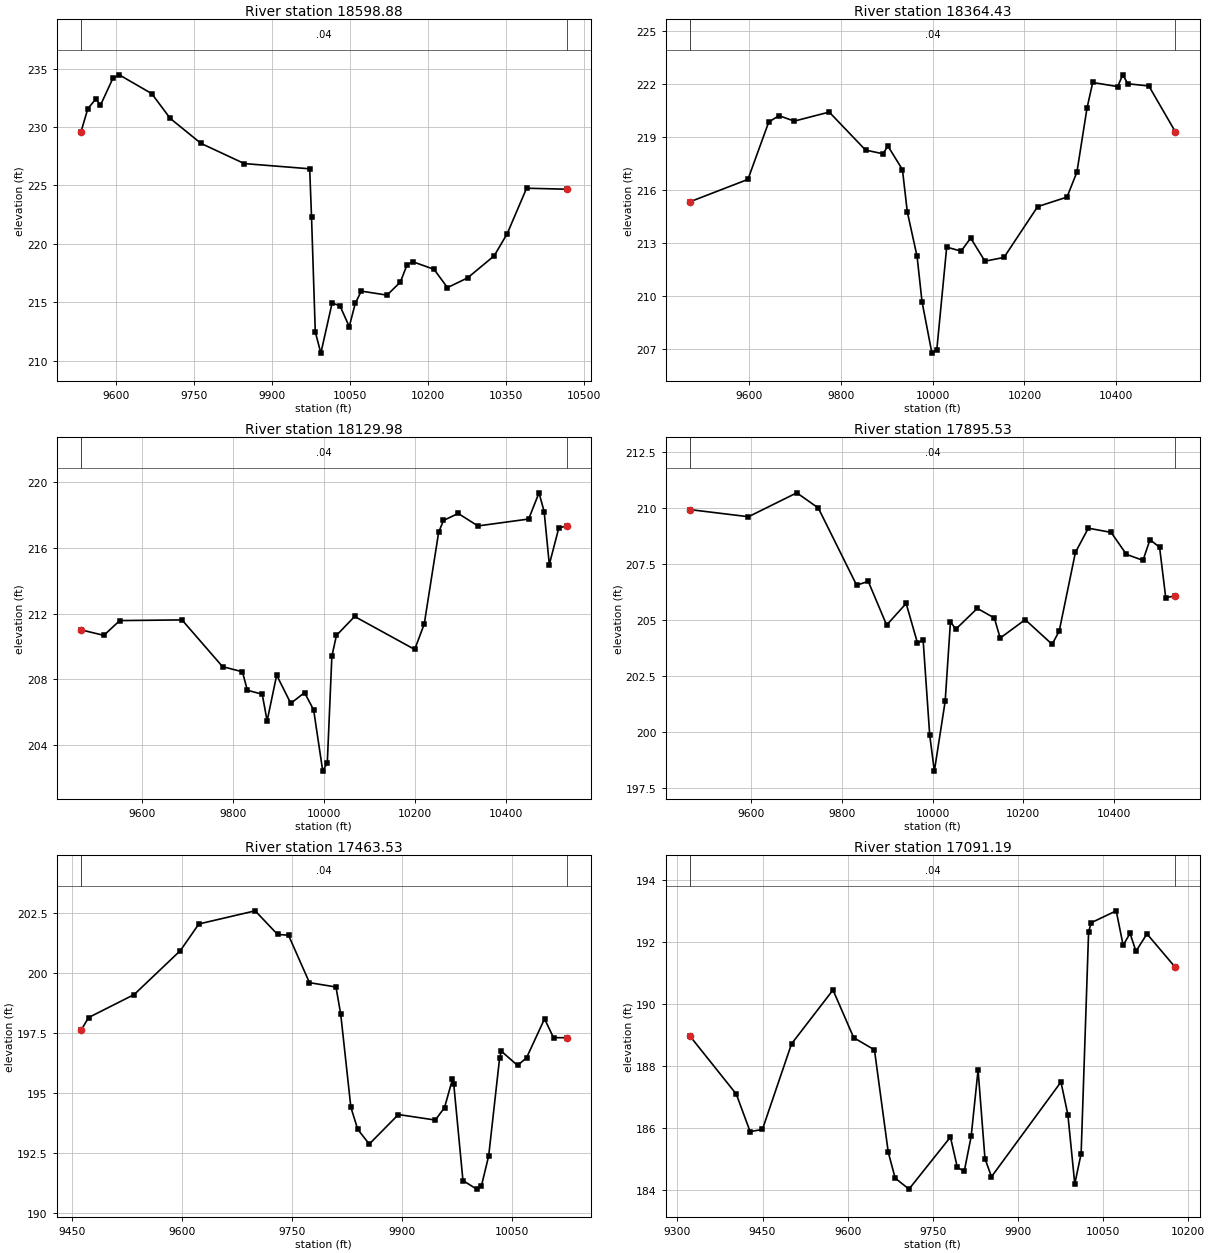
Type RM Length L Ch R = 1 ,18598.88,234.452000,234.452000,234.452000
XS GIS Cut Line= 6
897735.737069624803601.050557999 897447.16370491803408.971468116
897392.696569033803378.967926832897268.126475941803321.417615635
 897091.20890494803178.862868789896962.263433365803085.457439383
#Sta/Elev= 30
9533.556229.59919546.518231.56519562.207232.40779570.662231.84149594.806234.1722
9606.879234.46389669.309232.8556 9705.01230.72559763.817 228.5989847.241226.8641
9972.856226.41779976.378222.33329983.616212.44759994.343210.634610015.87214.9135
10030.87214.7017 10048.9212.902610060.44 214.89310071.98215.946110121.46215.5998
10147.11216.717710160.04218.207910171.24 218.45510211.75217.811310237.61 216.244
10276.39217.080110327.37218.964910352.31220.853610389.67224.754710466.38224.6693
#Mann= 3 , 0 , 0
9533.556    0.04       09533.556    0.04       010466.38    0.04       0
#XS Ineff= 2 , 0
       0                               0
Bank Sta=9533.556,10466.38
Exp/Cntr=0.3,0.1

Type RM Length L Ch R = 1 ,18364.43,234.452100,234.452100,234.452100
XS GIS Cut Line= 6
897894.956651735803350.669216264897644.778977453803220.412208475
897375.022199434803120.779424867897162.613865676803058.554467899
897067.716565573803017.720689313896924.618905155802941.575110729
#Sta/Elev= 30
9471.583215.33689598.107 216.6069643.379219.84699665.609220.21149698.953219.9022
9775.094220.41319854.181218.26419892.188218.0536 9902.76 218.4949934.473217.1608
9945.045214.77089966.322212.2528 9977.09209.69389998.625206.779810009.34206.9833
10030.81212.773410062.27212.5501   10083213.2877 10114.1211.979510155.57212.1926
10228.82215.064710292.68 215.605 10314.3217.017210336.27220.637810348.69222.0881
10402.89 221.85410414.09222.519710425.29222.013610470.88221.889810528.37219.3074
#Mann= 3 , 0 , 0
9471.583    0.04       09471.583    0.04       010528.37    0.04       0
#XS Ineff= 2 , 0
       0                               0
Bank Sta=9471.583,10528.37
Exp/Cntr=0.3,0.1

Type RM Length L Ch R = 1 ,18129.98,234.452000,234.452000,234.452000
XS GIS Cut Line= 6
897887.972840851803109.359270873897528.319320519802922.829281962
897462.955098218802905.226081783897312.412815308802905.240281114
897202.163117712802883.892053826896901.634749716802746.947835107
#Sta/Elev= 30
9466.251211.01699516.345210.68099551.316211.58079688.192211.62139777.427208.7763
9821.053208.46529831.942207.33889864.608207.10039875.371205.47229896.394208.2599
9927.436206.54159957.676207.1986  9977.7 206.1429997.731202.417910007.75202.9378
10017.76209.404510027.77210.675610067.81211.831110199.93209.823810220.94 211.376
10252.57216.953810263.12 217.67310295.56218.103810338.93217.340810450.54 217.762
10473.22219.356710484.56218.218110495.91214.990210516.69217.209710533.75217.3497
#Mann= 3 , 0 , 0
9466.251    0.04       09466.251    0.04       010533.75    0.04       0
#XS Ineff= 2 , 0
       09611.179                       0
Bank Sta=9466.251,10533.75
Exp/Cntr=0.3,0.1

Type RM Length L Ch R = 1 ,17895.53,432.000000,432.000000,432.000000
XS GIS Cut Line= 6
897952.798683337803093.003001247897614.204455982802865.577372907
897563.931535639802812.450772054897470.986003897802674.631763022
897415.140114835802610.495400335897146.643977732802402.924396134
#Sta/Elev= 30
9463.727209.93279593.382209.61389700.105210.68049747.537210.00579832.281206.5602
9857.972206.72869898.602204.78029941.713205.74419966.769203.97889979.207204.1129
9993.712 199.88110004.03198.2619 10027.9201.376410039.63204.930210051.36204.5945
10098.88 205.525 10136.6205.094510149.43204.1992 10204.7205.019910264.24203.9216
10279.91204.514810315.68208.021210344.15209.103210394.59208.9148 10428.3207.9347
10464.96207.667310480.44208.588510501.62208.252910515.25205.999910536.26206.0831
#Mann= 3 , 0 , 0
9463.727    0.04       09463.727    0.04       010536.26    0.04       0
#XS Ineff= 2 , 0
       0  9656.8                       0
Bank Sta=9463.727,10536.26
Exp/Cntr=0.3,0.1

Type RM Length L Ch R = 1 ,17463.53,372.338100,372.338100,372.338100
XS GIS Cut Line= 6
898141.185810764802802.442945139897995.779905092802615.382076242
897945.886290922802559.968028058897905.346657045802521.299325276
897855.913329056802480.394172654897670.541672247802343.552922735
#Sta/Elev= 30
9462.193197.60489472.353198.13769534.605199.09629597.634200.92539622.846202.0335
9699.647202.58099730.188 201.5999745.133201.56559773.699199.59129809.873199.4104
9816.382198.27499830.173194.40549839.604193.4847 9855.29192.87289895.035194.1028
9945.339193.87269957.914194.38929968.746195.5701 9970.49195.37849983.066191.3562
10001.71190.997710008.23191.126510018.18192.382510033.05196.446710035.39196.7398
10057.57196.145710069.83196.465210094.35198.084110106.61197.301510124.33197.2997
#Mann= 3 , 0 , 0
9462.193    0.04       09462.193    0.04       010124.33    0.04       0
#XS Ineff= 2 , 0
       09671.568                       0
Bank Sta=9462.193,10124.33
Exp/Cntr=0.3,0.1

Type RM Length L Ch R = 1 ,17091.19,450.058200,450.058200,450.058200
XS GIS Cut Line= 3
898407.885408328802702.284102844897959.968741661802056.450769511
897906.519263815802012.433552461
#Sta/Elev= 30
9321.899188.97119403.781  187.099428.121185.87839449.791185.94579501.139188.7145
9574.157 190.4569610.666188.91299647.175  188.529671.514185.20999683.684184.3725
9708.023184.01789781.041   185.79793.211184.72089805.381184.5937 9817.55185.7202
 9829.72187.8701 9841.89185.00119853.371184.41819975.756187.48069987.926186.4231
 10000.1184.185810011.29185.167510024.43192.325910028.84192.627910073.11193.0141
10085.28191.899810097.45192.287510107.86191.705810127.25192.2692 10177.1191.1898
#Mann= 3 , 0 , 0
9321.899    0.04       09321.899    0.04       0 10177.1    0.04       0
#XS Ineff= 2 , 0
       09570.636                       0
Bank Sta=9321.899,10177.1
Exp/Cntr=0.3,0.1