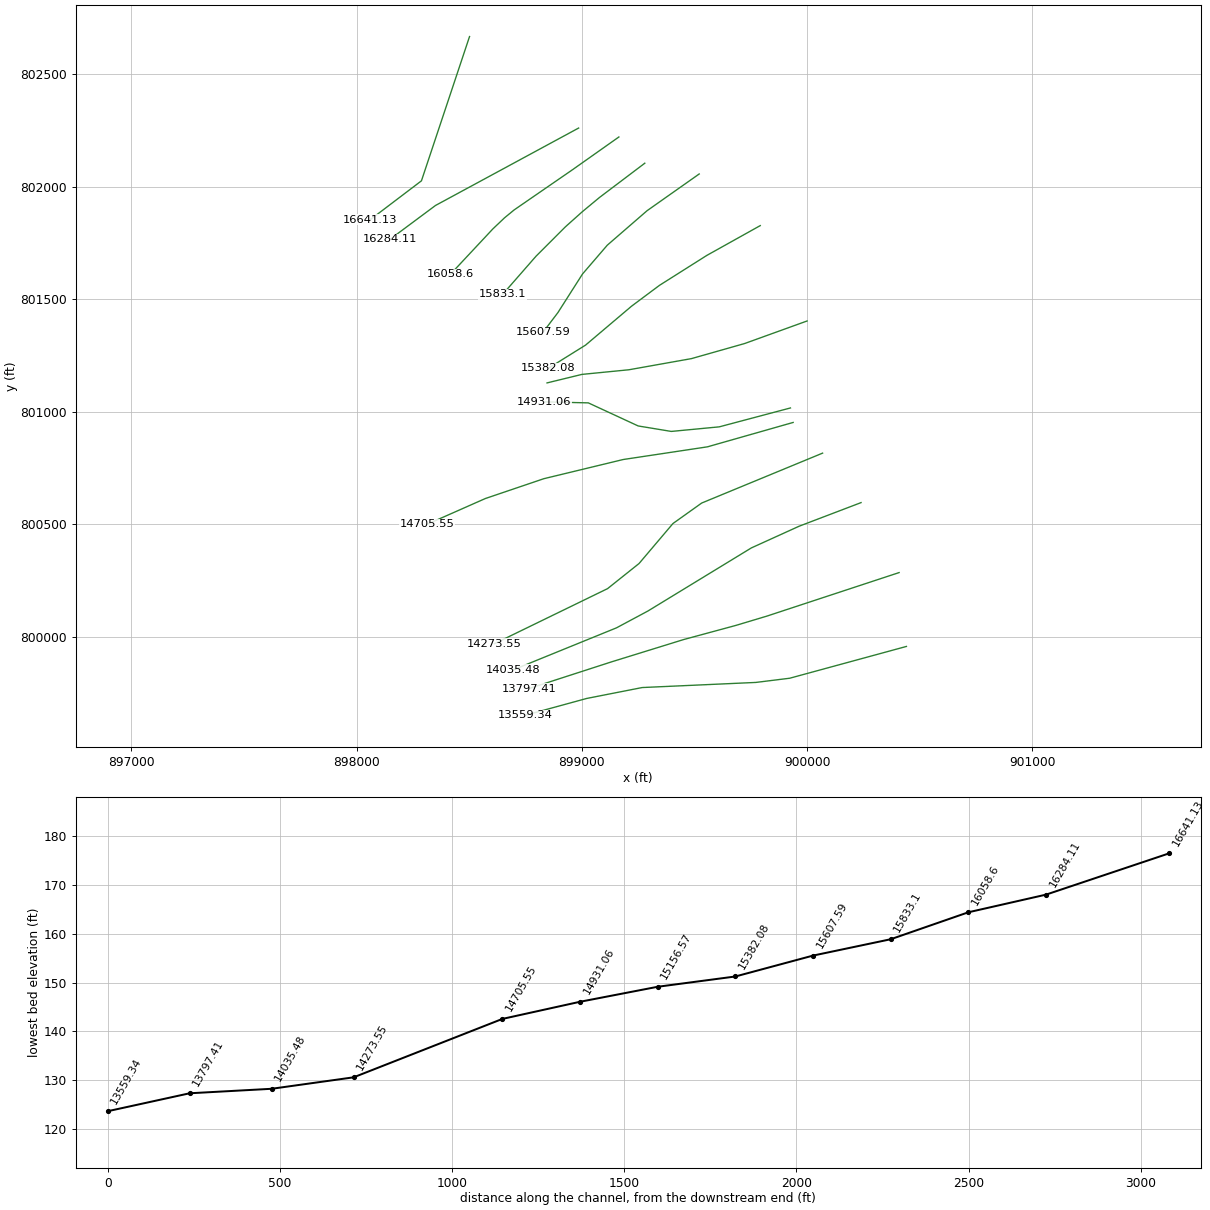
HEC-RAS study 11954_ras.prj: 11954

--- 11954_ras.g01 (geometry) --- (continued)

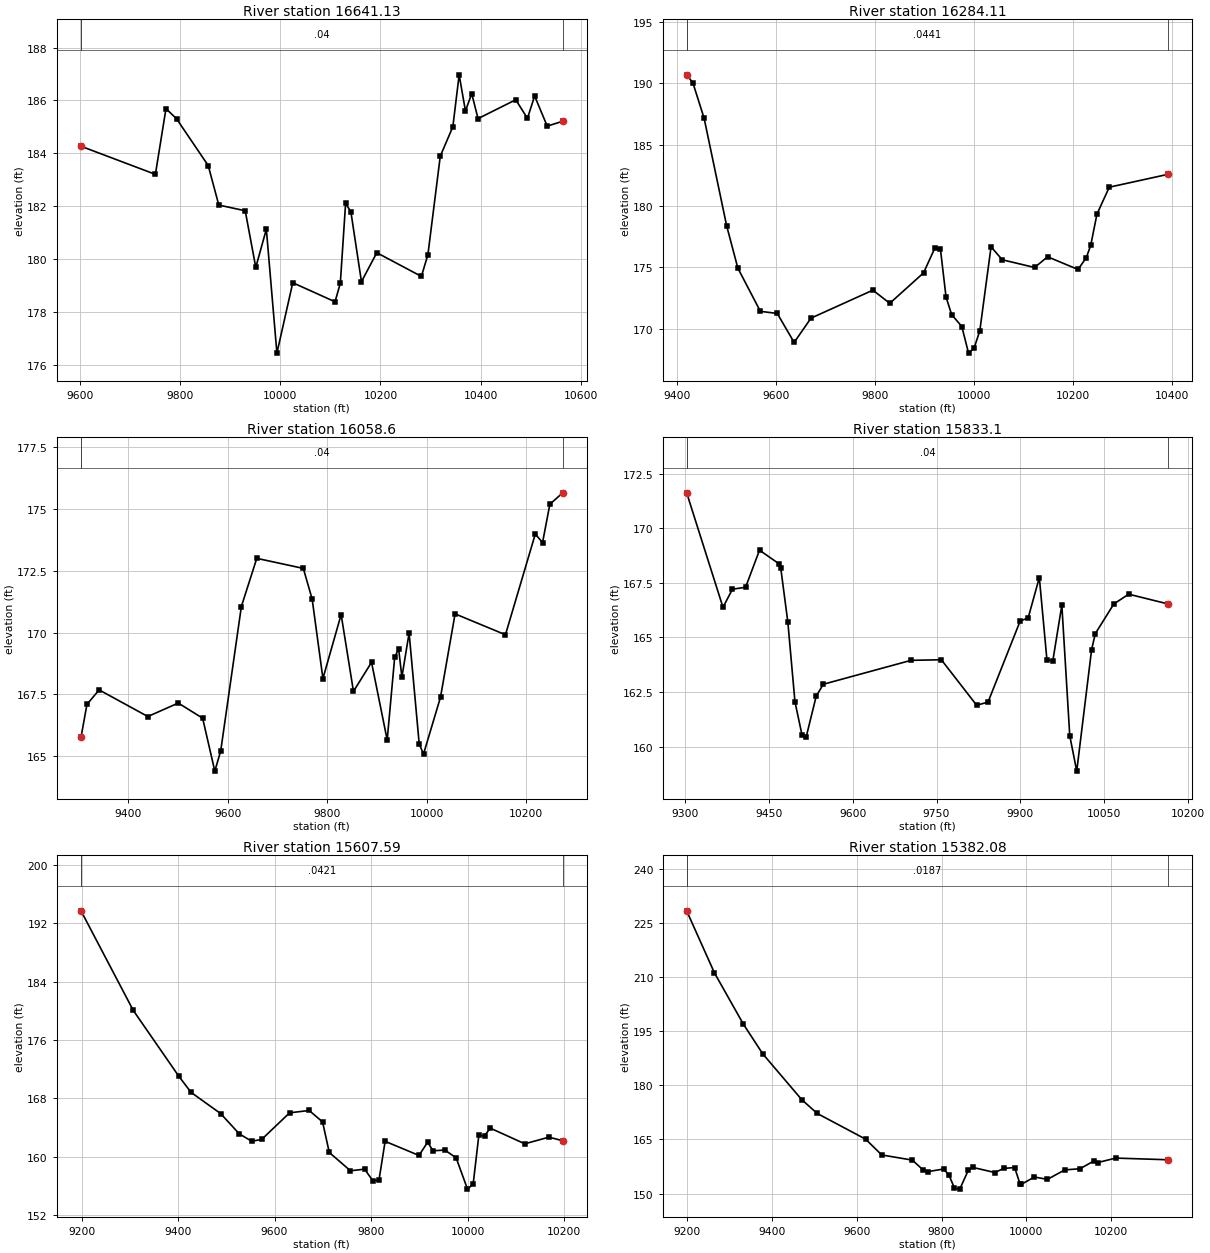
Type RM Length L Ch R = 1 ,16641.13,357.015600,357.015600,357.015600
XS GIS Cut Line= 3
898501.635408328802665.825769511898288.093741661802025.200769511
898060.457024223801852.510845938
#Sta/Elev= 30
9602.504184.27159750.947183.21029772.029185.69129793.111185.31099856.356183.5407
9877.438182.05119930.143 181.8359951.225179.69669972.306181.13879993.388176.4585
10025.01179.117310109.34178.397610119.88179.097510130.42182.112510140.96181.7979
10162.04179.1576 10192.7180.250810281.66179.355610294.66180.180410319.32183.8976
10344.42185.008310356.98186.969310369.53185.606310382.08186.258710394.63185.3154
10469.94186.027110493.21185.3259 10507.6  186.17 10532.7 185.03110563.51 185.216
#Mann= 3 , 0 , 0
9602.504    0.04       09602.504    0.04       010563.51    0.04       0
#XS Ineff= 2 , 0
       09810.704                       0
Bank Sta=9602.504,10563.51
Exp/Cntr=0.3,0.1

Type RM Length L Ch R = 1 ,16284.11,225.508800,225.508800,225.508800
XS GIS Cut Line= 3
898986.010408328802259.575769511898350.593741661801915.825769511
898149.218496082801766.085202286
#Sta/Elev= 30
9419.118190.68499431.637190.03959454.376187.14739499.854178.39839522.593174.9309
9568.071171.4176 9602.18171.24499636.288168.88329670.397170.86419795.462173.1425
 9829.57172.07189897.787174.54849920.527176.56019931.896176.50759943.266172.5827
9954.635171.14889975.162170.17949988.744168.012310000.11168.440410011.48169.8228
10034.22176.673410056.96175.616510122.28174.990210148.53175.861210209.98174.8285
10226.74175.792510235.76176.810110248.22179.335610273.14  181.53 10392.5182.5849
#Mann= 3 , 0 , 0
9419.118  0.0441       09419.118  0.0441       0 10392.5  0.0441       0
#XS Ineff= 2 , 0
       0 9791.32                       0
Bank Sta=9419.118,10392.5
Exp/Cntr=0.3,0.1

Type RM Length L Ch R = 1 , 16058.6,225.508800,225.508800,225.508800
XS GIS Cut Line= 6
899164.779217355802219.907549987898959.564430159802075.018108845
 898699.60476583801895.976644067898656.840011489801860.783363972
898604.831529167801811.307034939898417.432694726801610.902889548
#Sta/Elev= 30
9304.945165.76389316.916167.09639341.398167.68319439.329166.60559500.535167.1509
  9549.5166.53789573.984164.39679585.849165.21399627.379171.05599658.379173.0046
9751.966172.59759769.764  171.359791.353168.1413 9827.98170.73139852.759167.6222
9889.107 168.7999920.581165.65559935.608168.99469943.559169.35219950.116   168.2
9964.625169.98719984.965165.49299993.642165.089610027.77167.387510057.08170.7584
10158.35169.912910218.31173.986210232.97 173.64410247.63 175.19210273.38175.6548
#Mann= 3 , 0 , 0
9304.945    0.04       09304.945    0.04       010273.38    0.04       0
#XS Ineff= 2 , 0
       09735.188                       0
Bank Sta=9304.945,10273.38
Exp/Cntr=0.3,0.1

Type RM Length L Ch R = 1 , 15833.1,225.508800,225.508800,225.508800
XS GIS Cut Line= 6
899279.839107473802103.470024699899078.824494466801951.475071112
899002.858113207801888.486257207898926.844637238801820.587637035
898797.058017448801690.748673112898649.190100508801521.606919391
#Sta/Elev= 30
9303.424171.63149368.329166.38289385.201167.2116 9408.76167.30279433.602169.0012
9468.291168.38129471.612168.17899484.282165.69929496.952 162.0569509.622160.5229
9517.146160.44919534.963162.30949547.633162.85479704.407163.95159758.628163.9781
9821.685161.89369842.043162.03549899.473165.7505 9913.86165.9006 9933.76167.7483
9947.337163.97759957.908163.93179973.999166.48339988.153160.495710000.62158.8721
10027.15164.433910033.78165.175210066.96166.537210093.49166.984410164.34166.5335
#Mann= 3 , 0 , 0
9303.424    0.04       09303.424    0.04       010164.34    0.04       0
#XS Ineff= 2 , 0
       09680.513                       0
Bank Sta=9303.424,10164.34
Exp/Cntr=0.3,0.1

Type RM Length L Ch R = 1 ,15607.59,225.508800,225.508800,225.508800
XS GIS Cut Line= 6
899521.354013453802055.653613282 899290.06873554801892.678006084
899113.296234119801739.496835731899003.491444511801611.858729157
898894.082630932 801440.25190451 898828.06225288801353.141899395
#Sta/Elev= 30
9198.769193.7305 9307.12180.05879401.299171.04199427.022168.80049488.284165.8941
9526.919163.11059552.675162.09729573.294162.34559631.228165.99989671.781166.3201
9699.555164.74649713.442160.55619757.351158.04419786.713158.26529803.684 156.678
9816.453156.74649829.222 162.0869899.411160.14839917.198161.95089928.876160.7844
9952.973160.89139976.477159.81639999.975155.523310011.73156.228510023.49162.9005
10035.25162.8204   10047163.900610118.79161.744610168.67162.656510197.26162.1719
#Mann= 3 , 0 , 0
9198.769  0.0421       09198.769  0.0421       010197.26  0.0421       0
#XS Ineff= 2 , 0
       09668.819                       0
Bank Sta=9198.769,10197.26
Exp/Cntr=0.3,0.1

Type RM Length L Ch R = 1 ,15382.08,225.508800,225.508800,225.508800
XS GIS Cut Line= 6
899792.410354231801826.384839584899555.090465653801693.999509321
899345.011242982801561.162545335899221.255098511 801468.80649322
899016.889178961801295.887489536898852.096145508801193.220806673
#Sta/Elev= 30
9198.379228.30919263.826211.15579332.226  196.939377.988188.70439470.245175.9909
9506.745172.18769620.878165.07019658.873160.70499731.072159.27679755.718156.6408
9768.041156.09199805.063156.81699817.737155.06239830.549151.52939843.086151.2421
9863.101156.45179873.181157.27649925.874155.8391 9946.52156.97289972.594157.2235
9985.631152.5618 9988.22152.549710019.17154.604510049.94153.938910090.74156.5652
10126.87156.889510159.13159.003510168.17158.583410211.13159.838210335.37159.3688
#Mann= 3 , 0 , 0
9198.379  0.0187       09198.379  0.0187       010335.37  0.0187       0
#XS Ineff= 2 , 0
       0                               0
Bank Sta=9198.379,10335.37
Exp/Cntr=0.3,0.1

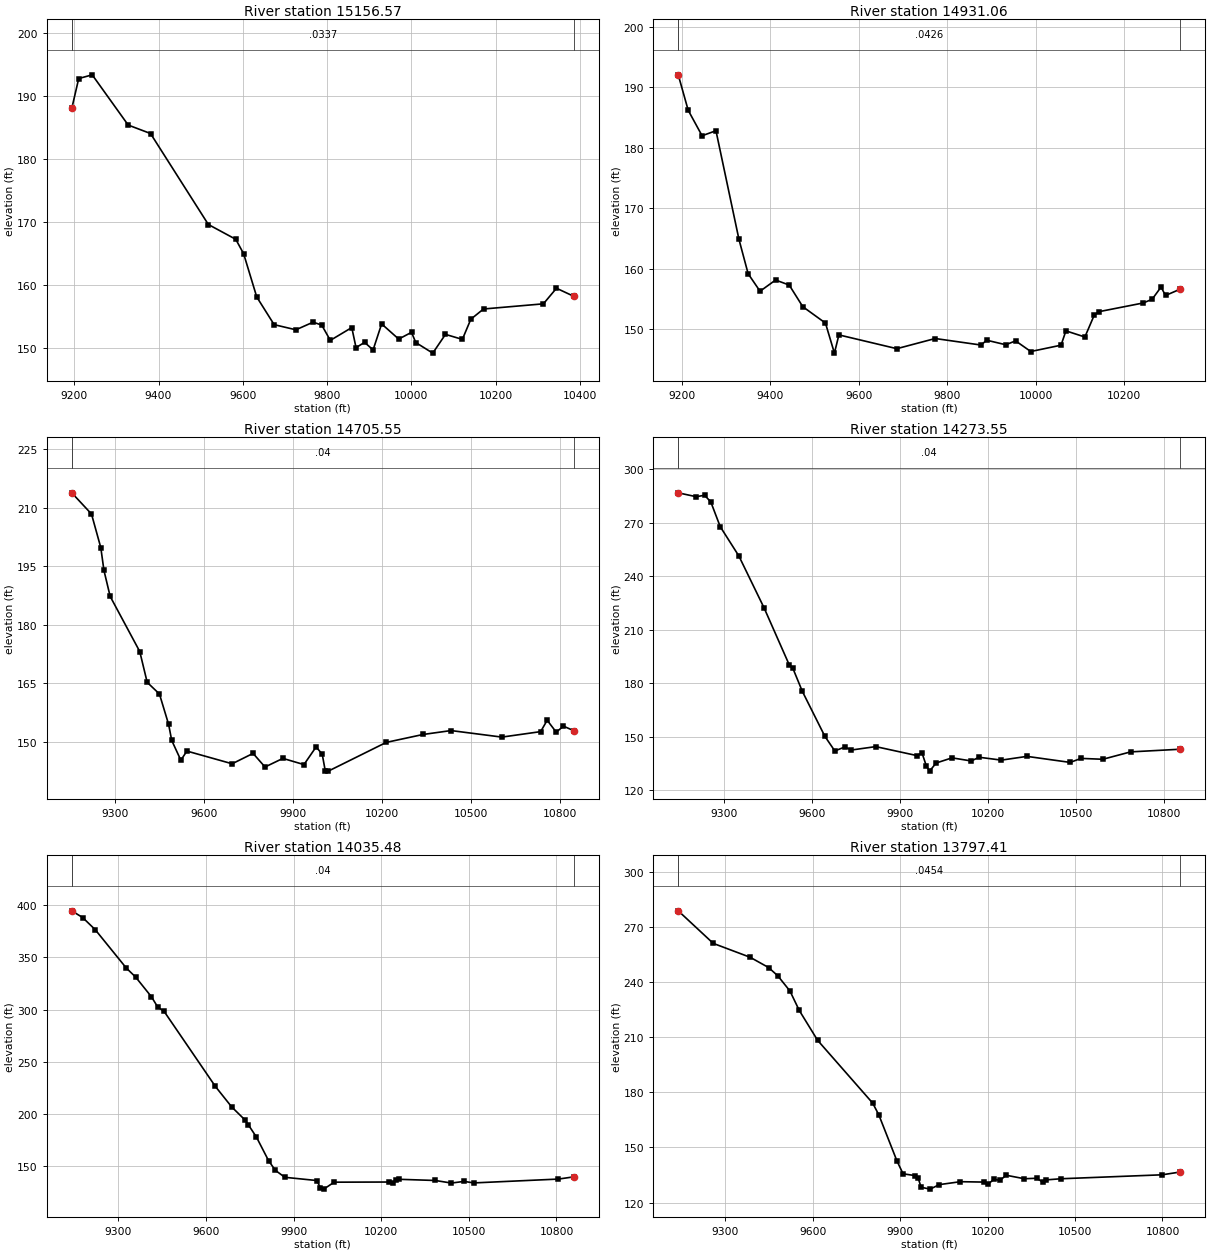
Type RM Length L Ch R = 1 ,15156.57,225.508800,225.508800,225.508800
XS GIS Cut Line= 6
900000.405662798801402.961238635899723.078609244801302.808399324
899486.792544891801235.786734045899209.241251678 801186.30802807
899000.605197209801165.721566006898845.669009378801127.930670836
#Sta/Elev= 30
9194.084187.97679210.545 192.724  9242.6193.31489328.037185.34089381.001183.9996
9518.344169.5545  9583.4167.20649602.055164.92029633.199158.05059674.514 153.656
9726.157152.8398 9767.07154.05189787.474153.58649807.879151.16029858.802 153.194
9868.929150.01029889.182150.84319909.435149.65129929.688153.77489970.194151.3677
 10000.6152.436210010.77150.816210051.07149.136210081.23152.111810121.36151.3182
10141.42154.520110171.52156.1413 10313.7156.962110344.76159.436710385.99 158.152
#Mann= 3 , 0 , 0
9194.084  0.0337       09194.084  0.0337       010385.99  0.0337       0
#XS Ineff= 2 , 0
       0                               0
Bank Sta=9194.084,10385.99
Exp/Cntr=0.3,0.1

Type RM Length L Ch R = 1 ,14931.06,225.508800,225.508800,225.508800
XS GIS Cut Line= 6
899926.504485956801016.796706378899610.383640497800932.866186098
899397.512148891800912.535252684899250.427017972800936.840588084
899028.903649665801039.334892947898831.871470778801043.891117544
#Sta/Elev= 30
9192.386 192.0399214.876186.18389246.251181.97349277.627182.80419329.582164.8541
9350.335159.1793 9377.27156.28739412.331158.13829443.096157.31259473.861 153.733
 9525.06151.02469545.287146.0624  9555.4149.07449686.334146.79669772.981148.4763
9876.703147.39679889.199148.19949932.488147.44669954.668148.08729988.984146.3291
10057.42147.375710068.35149.743210111.24148.726710132.13152.297210142.36152.9007
 10243.2154.351210263.22154.962210283.33156.977610293.43155.587110326.87156.6381
#Mann= 3 , 0 , 0
9192.386  0.0426       09192.386  0.0426       010326.87  0.0426       0
#XS Ineff= 2 , 0
       0                               0
Bank Sta=9192.386,10326.87
Exp/Cntr=0.3,0.1

Type RM Length L Ch R = 1 ,14705.55,432.000000,432.000000,432.000000
XS GIS Cut Line= 6
899938.417650932800952.393617667899558.054395577 800844.14969157
899183.924267233800787.825571512898831.425930615800702.633996015
  898572.0036278 800614.67397057898313.199814263800500.241309402
#Sta/Elev= 30
9153.071213.76779219.615208.34929251.093199.70929261.586193.92499282.572187.2683
9382.444173.15819407.493165.27639448.891 162.2829479.887 154.4919490.164150.4263
9520.996 145.3459541.551147.68119694.141144.43359764.757147.08699805.014143.6066
  9865.4145.80859936.379144.22339977.452148.74969997.988146.884410008.25142.6379
10018.53142.549610213.94149.899410338.44151.932610432.75152.928610604.05151.2572
10734.94 152.65810756.94 155.56810787.52152.520410811.94154.058810846.93152.8852
#Mann= 3 , 0 , 0
9153.071    0.04       09153.071    0.04       010846.93    0.04       0
#XS Ineff= 2 , 0
       0                10312.99       0
Bank Sta=9153.071,10846.93
Exp/Cntr=0.3,0.1

Type RM Length L Ch R = 1 ,14273.55,238.072000,238.072000,238.072000
XS GIS Cut Line= 6
900069.179816189800816.182020415899532.421555614800594.614859184
899404.825043565800503.635392548899254.292571923800326.106693338
899114.471101235800214.537065215 898612.47200258799970.279652924
#Sta/Elev= 30
9145.112286.85319206.556284.66579234.789285.50329256.095281.71149288.055267.8651
9351.593251.38569437.682222.16959523.738190.02979534.655188.65499567.524175.4417
9644.426150.13389678.325141.91599712.224144.12789735.127 142.4439817.782 144.344
9956.684139.35129975.553140.64189989.801133.5885   10001130.581910023.37135.1369
10077.44138.037510142.95136.288910169.56138.377110245.56136.761710332.76138.8611
10479.82135.477710516.69137.7315 10590.9137.238210685.52141.386710854.87142.8803
#Mann= 3 , 0 , 0
9145.112    0.04       09145.112    0.04       010854.87    0.04       0
#XS Ineff= 2 , 0
       0                10258.25       0
Bank Sta=9145.112,10854.87
Exp/Cntr=0.3,0.1

Type RM Length L Ch R = 1 ,14035.48,238.071900,238.071900,238.071900
XS GIS Cut Line= 6
900239.993020908800596.486801521899965.034762624800491.699349645
899752.925766795800395.350522247899293.767300314800115.252068025
899154.483743487800040.648843943898695.575629969799853.891151482
#Sta/Elev= 30
9140.489394.5835 9177.82 388.1339220.492376.63719327.178339.83249359.463331.0913
 9413.27 312.3279434.794302.49379456.588298.36169632.158226.51889688.075206.9007
9732.395194.75679744.709189.9533 9772.94177.95059814.184155.55549837.367146.2642
9869.933139.55369979.559136.45419991.409129.707210003.25128.2334 10038.9134.8877
10226.65135.029910238.89133.832810250.38136.842710261.87 137.634 10385.3136.5039
 10440.3134.039810483.79135.6358 10516.8134.175810806.75137.860410859.52139.9846
#Mann= 3 , 0 , 0
9140.489    0.04       09140.489    0.04       010859.52    0.04       0
#XS Ineff= 2 , 0
       0                10285.29       0
Bank Sta=9140.489,10859.52
Exp/Cntr=0.3,0.1

Type RM Length L Ch R = 1 ,13797.41,238.072000,238.072000,238.072000
XS GIS Cut Line= 6
900409.013643304800285.851172042899821.552660451800092.469244295
899684.187300637800051.255841534899452.285643133799988.483316074
899130.071871177799888.798232638898765.596562714799770.873103216
#Sta/Elev= 30
9138.742278.97579258.884261.22999385.334253.67459448.559248.08719480.172243.5878
9522.023235.28349553.934 224.694 9617.04208.38579805.822174.19519826.703167.8597
9889.345142.57579910.127135.6626 9951.46134.68719961.794133.32289972.127128.3194
10003.14127.312810034.15129.762610106.82131.366710186.52131.155110200.87129.8629
 10221.8  132.7110242.74 132.07310263.67134.886110326.48132.965610368.35133.2398
10389.28131.143210399.75 132.33710452.09132.966810798.83135.118910861.26136.6464
#Mann= 3 , 0 , 0
9138.742  0.0454       09138.742  0.0454       010861.26  0.0454       0
#XS Ineff= 2 , 0
       0                10301.34       0
Bank Sta=9138.742,10861.26
Exp/Cntr=0.3,0.1

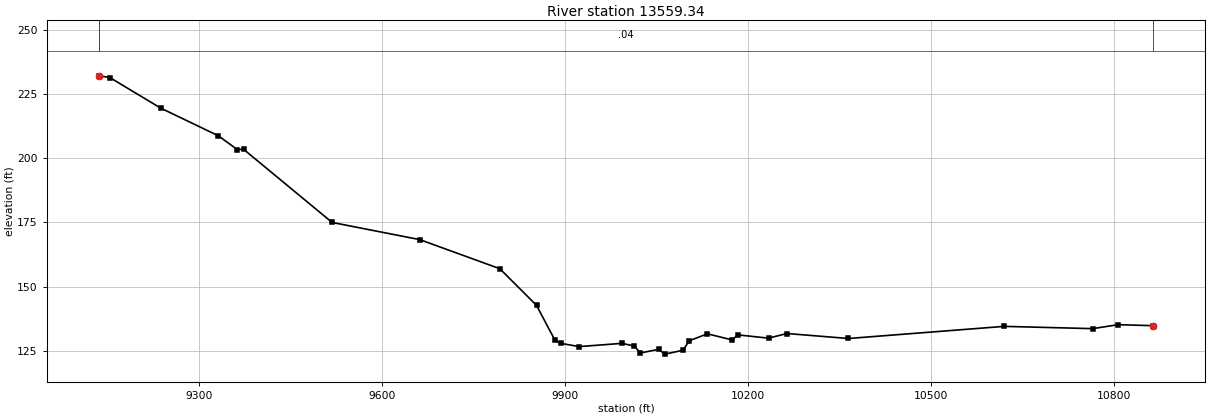
Type RM Length L Ch R = 1 ,13559.34,238.071900,238.071900,238.071900
XS GIS Cut Line= 6
900441.411507119 799957.89259431 899923.25144423799816.766230287
899773.043028853799798.116452849899268.251628348799775.383115121
899022.337874787799727.073401209898750.315895989799652.731001597
#Sta/Elev= 30
9136.412232.13769153.567231.47549237.189219.53339331.265208.7972 9362.55203.4129
9372.955203.47869518.106174.97149661.737168.28449793.062156.93359853.234142.6435
9883.259129.1187 9893.26127.82169923.263126.56929993.344 127.83410013.42126.8166
10023.45124.0799 10053.5125.4959 10063.5123.6345 10093.5125.1493 10103.5128.8436
 10133.5131.552410173.51129.190310183.52131.1332 10233.6 129.86310263.69131.6697
10364.56129.727610620.12134.457210765.15133.569110806.73135.115410863.58134.7318
#Mann= 3 , 0 , 0
9136.412    0.04       09136.412    0.04       010863.58    0.04       0
#XS Ineff= 2 , 0
       0                10224.87       0
Bank Sta=9136.412,10863.58
Exp/Cntr=0.3,0.1