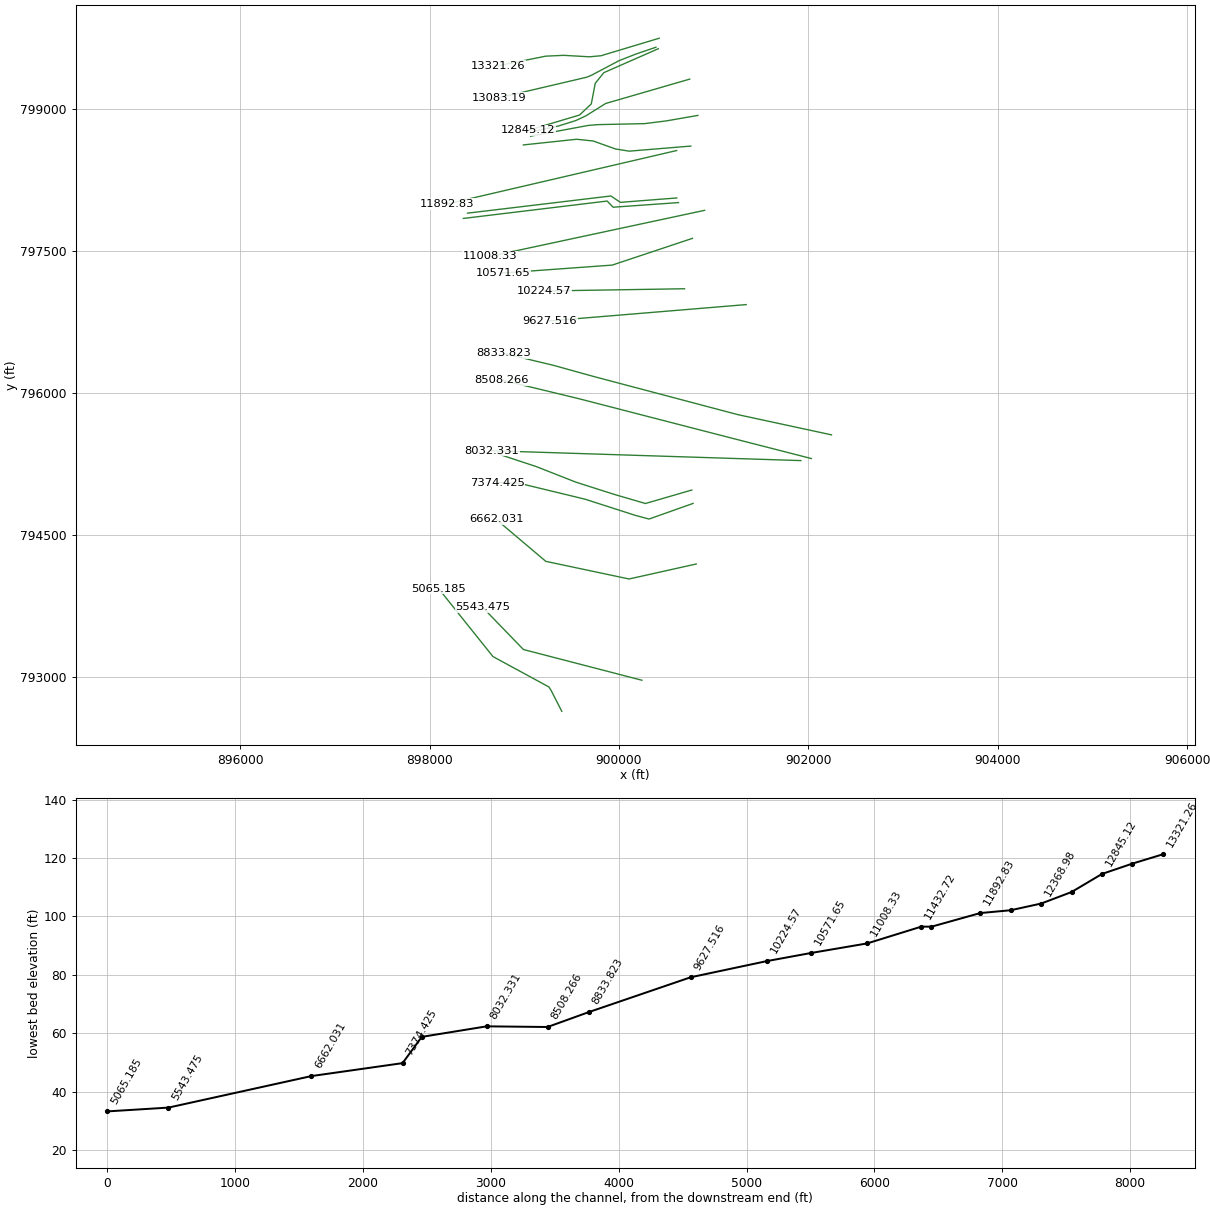
HEC-RAS study 11954_ras.prj: 11954

--- 11954_ras.g01 (geometry) --- (continued)

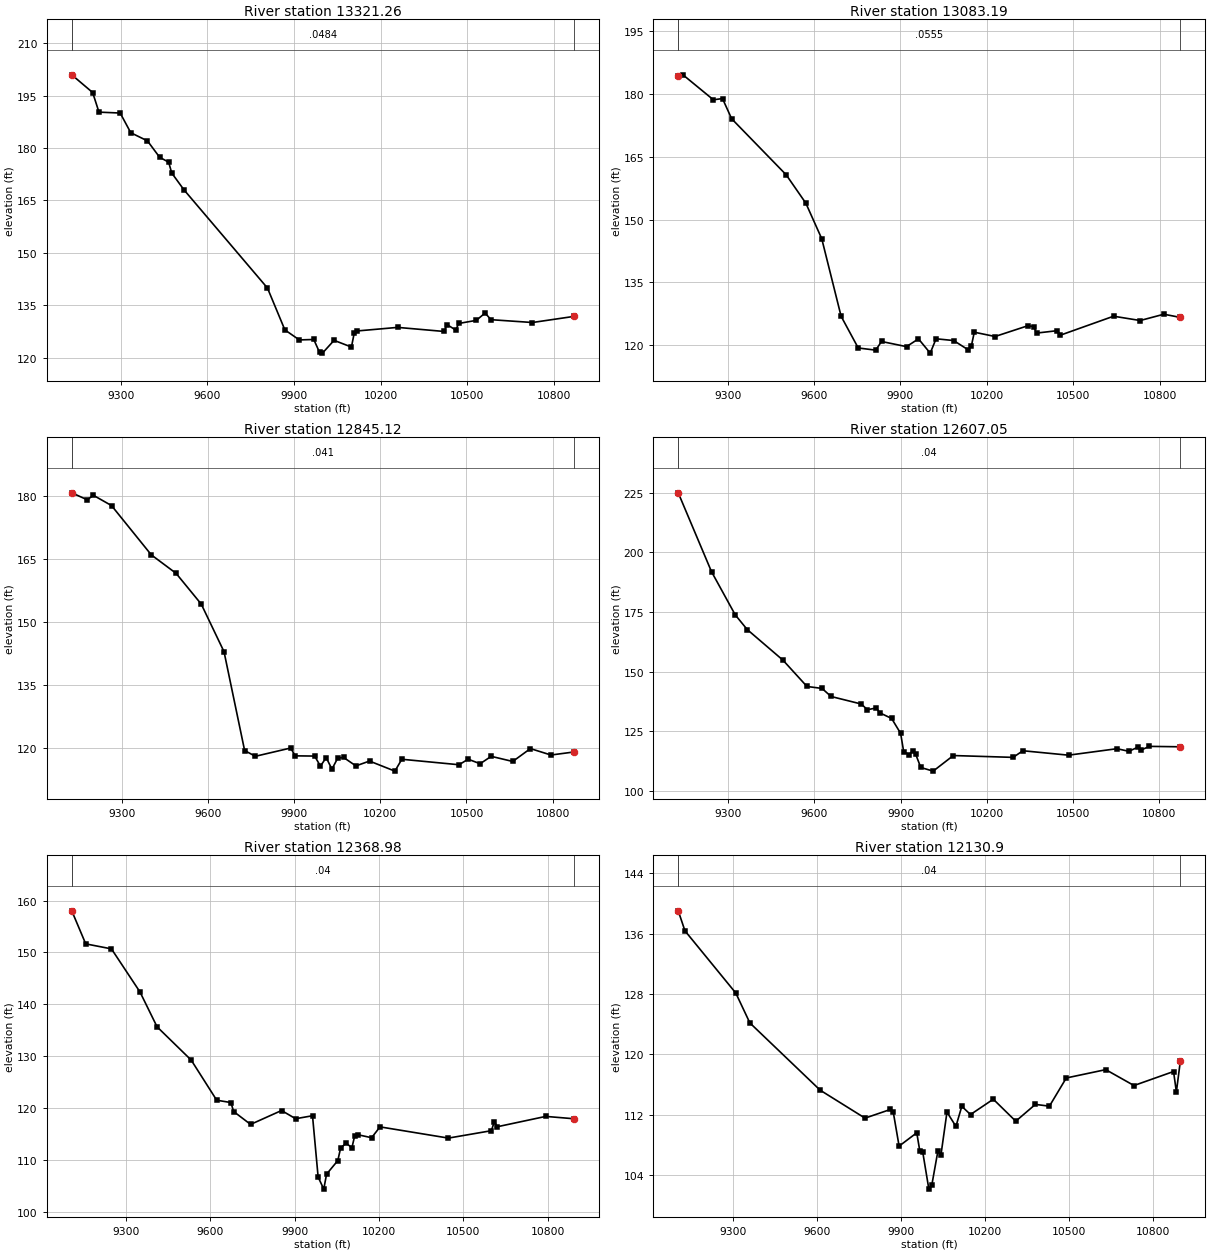
Type RM Length L Ch R = 1 ,13321.26,238.072000,238.072000,238.072000
XS GIS Cut Line= 6
900424.724253498799746.934876279899809.349431194799561.947508563
899689.789188248799550.942337841899416.303522318799566.382645833
 899228.05389853799557.866318335898725.776546522799456.944018811
#Sta/Elev= 30
9130.828200.94099203.171195.87149224.985 190.2599298.443190.00269335.093184.3663
9392.889182.02929434.865177.35859466.347175.92449476.841172.84279518.817168.0644
9808.397139.8987 9868.65 127.9189918.694125.04719968.753125.16819988.804121.4618
9998.829121.264510038.95124.924510099.13123.004810109.13127.159610119.14127.6135
10259.19128.632510420.02127.465310430.11129.425610460.37127.871310470.46129.7599
10531.41130.6416 10561.9132.748810582.29130.838610725.74130.030510869.18131.7758
#Mann= 3 , 0 , 0
9130.828  0.0484       09130.828  0.0484       010869.18  0.0484       0
#XS Ineff= 2 , 0
       0                10220.71       0
Bank Sta=9130.828,10869.18
Exp/Cntr=0.3,0.1

Type RM Length L Ch R = 1 ,13083.19,238.072000,238.072000,238.072000
XS GIS Cut Line= 6
900390.550707294799651.930211096900177.729559907 799579.45260493
900000.053217033799509.596174728899710.271107433799356.373117272
899659.076398788799335.368482149898739.350110126799119.707310348
#Sta/Elev= 30
9128.051184.36819144.479184.60989250.119178.64569281.811178.93389313.503174.1169
9503.058160.70819571.292153.92849626.534145.43589693.834126.88829753.258119.3177
9813.938118.80329834.164120.87399920.931119.63719962.427121.500410003.32118.0885
10023.68121.516610084.77121.094710135.93118.847210146.17119.777610156.41 123.091
10228.51122.062910341.79124.619510362.39124.447910372.69122.879810444.78123.4551
10455.08122.370910640.19126.911410732.66125.882810814.85127.386710872.02126.6286
#Mann= 3 , 0 , 0
9128.051  0.0555       09128.051  0.0555       010872.02  0.0555       0
#XS Ineff= 2 , 0
       0                10197.88       0
Bank Sta=9128.051,10872.02
Exp/Cntr=0.3,0.1

Type RM Length L Ch R = 1 ,12845.12,238.071900,238.071900,238.071900
XS GIS Cut Line= 6
  900416.2559089799636.476964679899840.580429907 799383.61377356
899749.883003483799271.473298566899707.973624472 799053.26100046
899584.305236505 798936.44323061899036.858026294798773.062855866
#Sta/Elev= 30
9126.238180.80159180.251179.14039201.327180.21849264.578177.76699402.962166.0402
9489.186161.63989576.874 154.3149656.146142.98169727.866119.44569765.301118.0792
9888.358120.05279903.505118.1846 9971.69118.13139991.706115.738510011.71117.7627
10031.74115.024610051.87117.640610072.37117.802710115.08115.791410162.55 116.944
10250.91114.5466   10275117.371810474.08116.066110505.79117.388810547.52116.3043
10586.08118.067910661.06116.846610722.54119.911910794.07118.381910873.73119.1003
#Mann= 3 , 0 , 0
9126.238   0.041       09126.238   0.041       010873.73   0.041       0
#XS Ineff= 2 , 0
       0                10336.79       0
Bank Sta=9126.238,10873.73
Exp/Cntr=0.3,0.1

Type RM Length L Ch R = 1 ,12607.05,238.072000,238.072000,238.072000
XS GIS Cut Line= 6
900747.085210298799315.404946878 899859.60453569799058.114658463
899651.069345177 798927.56110337899544.672281709798877.948558427
899360.261105495798820.076173702899099.473592503798763.444913017
#Sta/Elev= 30
9125.417224.97459241.315191.93589324.037173.83389365.606167.70479490.385154.8404
9573.915143.82969626.316143.01829657.757139.64039763.235 136.474 9784.35134.0882
9816.023 134.8559826.581132.85679868.772130.42639900.212 124.1669910.693 116.577
9929.585115.27459941.897116.90949952.228115.54889970.355109.882510013.52108.3622
10083.78114.893310292.11114.124610326.02116.9038 10485.1115.0461 10654.1117.7642
10695.24116.661910725.92118.370710736.13117.106710766.75118.732810874.46118.5615
#Mann= 3 , 0 , 0
9125.417    0.04       09125.417    0.04       010874.46    0.04       0
#XS Ineff= 2 , 0
       0                10365.44       0
Bank Sta=9125.417,10874.46
Exp/Cntr=0.3,0.1

Type RM Length L Ch R = 1 ,12368.98,238.071900,238.071900,238.071900
XS GIS Cut Line= 6
900833.793620575798932.161793679900495.420013914798873.583848518
900270.426039352798845.392094191899778.094940477798834.930425834
899675.140249129798826.383750407899066.785574101798712.912458206
#Sta/Elev= 30
9107.461158.02669157.048151.6619 9248.51150.69769349.958142.39969410.766135.6815
9532.072129.27549622.769121.54779673.058121.0993  9683.1 119.3649743.269116.8866
 9853.37119.56449903.371117.98169963.372118.55549983.373106.748210003.37  104.42
10013.37107.301710053.37109.923810063.37112.365210083.37113.266110103.37 112.378
10113.37 114.67910123.37114.914510173.38114.322710203.43116.410410446.57114.2495
 10599.5115.6773 10609.7117.4293 10619.9116.431310792.81118.428610892.52117.9765
#Mann= 3 , 0 , 0
9107.461    0.04       09107.461    0.04       010892.52    0.04       0
#XS Ineff= 2 , 0
       0                 10271.5       0
Bank Sta=9107.461,10892.52
Exp/Cntr=0.3,0.1

Type RM Length L Ch R = 1 , 12130.9,238.072000,238.072000,238.072000
XS GIS Cut Line= 6
900758.693391825798608.448427272900108.550524068798554.828950322
899964.171351418798577.795609292899727.581612728798662.090376462
899552.950818756798680.507872507898991.079832184798620.690781308
#Sta/Elev= 30
9103.812139.02349127.713136.37629309.288128.12689359.554 124.1659610.479115.2525
9770.619111.54749861.467112.70029871.643112.30449892.284107.83989955.361109.6044
9966.092107.22199976.898106.99649998.509102.137610009.31102.722210030.85107.1955
10041.62106.647410063.16112.345110095.11110.450610116.15113.1138 10147.2112.0217
10228.56114.054410308.76111.1411 10378.8113.367210428.92113.133610489.14116.8703
10630.01 117.97510730.81 115.86810872.06117.725110882.15115.0285 10896.2119.0729
#Mann= 3 , 0 , 0
9103.812    0.04       09103.812    0.04       0 10896.2    0.04       0
#XS Ineff= 2 , 0
       0                10196.17       0
Bank Sta=9103.812,10896.2
Exp/Cntr=0.3,0.1

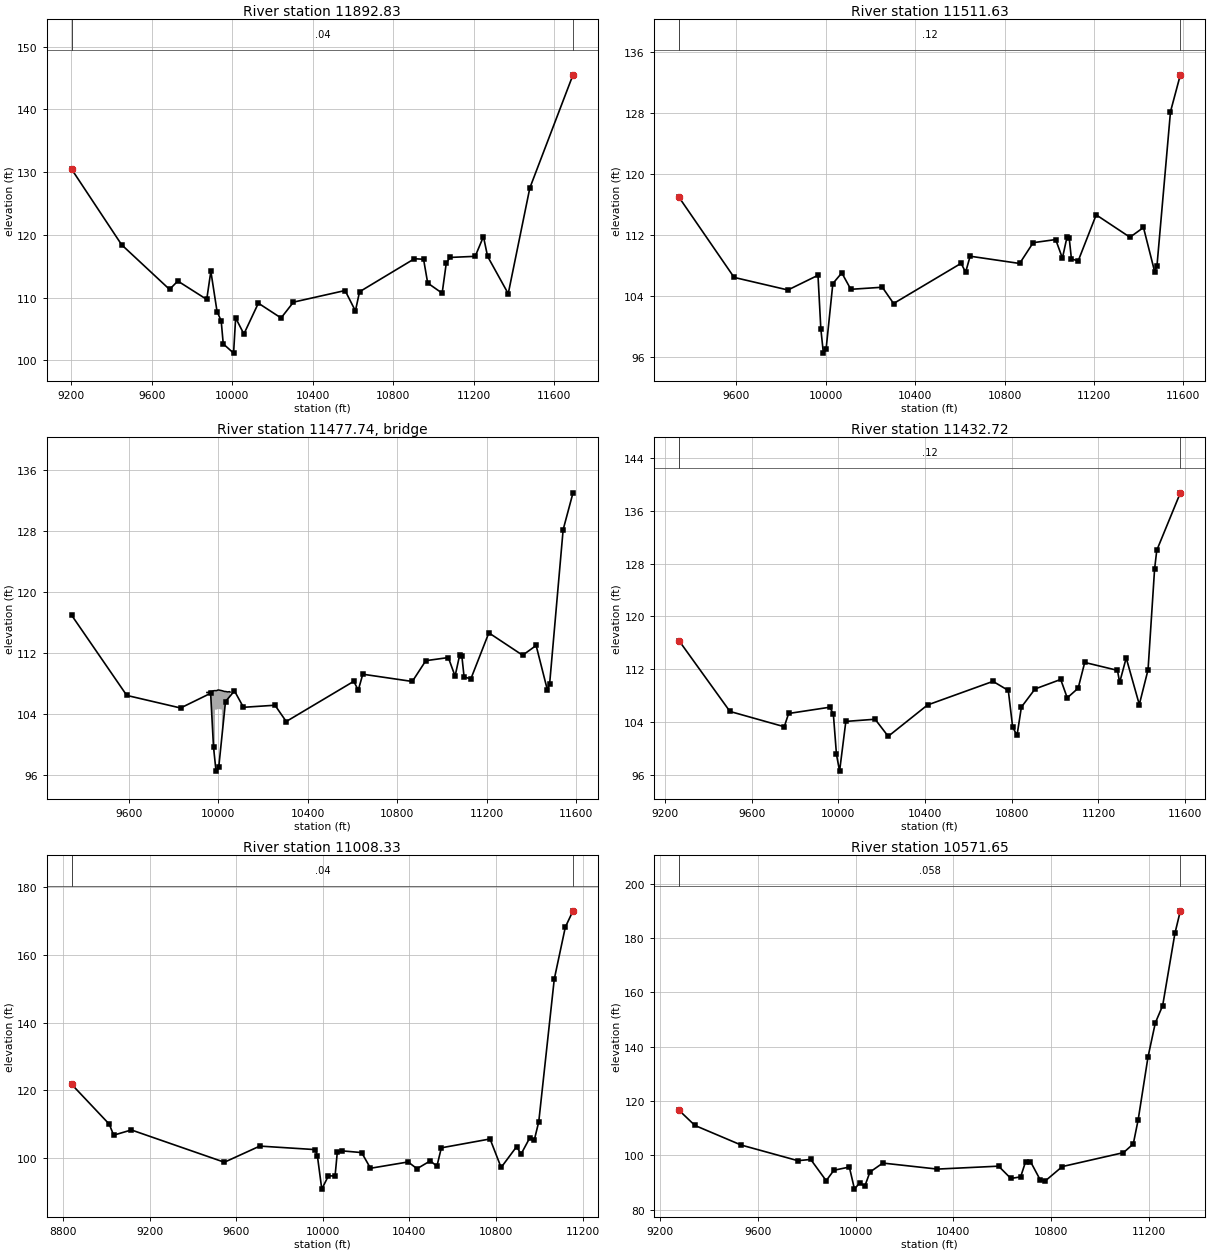
Type RM Length L Ch R = 1 ,11892.83,381.199400,381.199400,381.199400
XS GIS Cut Line= 2
900608.694202398798561.233421755898181.372988456797996.329575601
#Sta/Elev= 30
9201.169130.44229449.255118.43289687.523111.32119728.591112.65329872.333109.7248
9892.867114.20589923.669107.79379944.204 106.3149954.471102.643810005.81101.1694
10016.07106.776210057.14 104.21610129.01109.127610241.95106.767710303.56109.2927
10560.24111.141210611.57 107.88910632.11110.947310905.12116.208410950.39116.1236
10970.93112.3347 11042.8110.719911063.33115.516511081.59116.414311207.07116.5872
11248.14119.734211268.68116.584511371.35110.639211478.64127.472411693.36145.5044
#Mann= 3 , 0 , 0
9201.169    0.04       09201.169    0.04       011693.36    0.04       0
#XS Ineff= 2 , 0
       0                10263.31       0
Bank Sta=9201.169,11693.36
Exp/Cntr=0.3,0.1

Type RM Length L Ch R = 1 ,11511.63,78.912800,78.912800,78.912800
XS GIS Cut Line= 4
900610.463684887798060.760520712 900015.12422356 798014.24962528
899915.125798374798081.690423653898401.196152478797900.297931507
#Sta/Elev= 30
9343.765116.96289589.976106.45299830.708104.80119965.192106.73249978.02999.66528
9989.31596.5098710001.3897.0076110031.68105.644410071.73107.045610112.02104.8913
10253.02105.162610303.38 103.02510605.52108.303510625.67107.137310645.81109.2366
10867.38108.283810927.81111.013611028.53111.423111058.74108.983511078.88 111.711
11088.96111.642911099.03108.880311129.24108.618411209.81114.668111360.89111.7278
11421.32113.008511471.67107.167111481.74107.983211542.17128.214711586.29133.0557
#Mann= 3 , 0 , 0
9343.765    0.12       09343.765    0.12       011586.29    0.12       0
#XS Ineff= 2 , 0
       0                10562.63       0
Bank Sta=9343.765,11586.29
Exp/Cntr=0.3,0.1

Type RM Length L Ch R = 3 ,11477.74,,,
BEGIN DESCRIPTION:
END DESCRIPTION:
Bridge Culvert--1,0,-1,-1, 0
Deck Dist Width WeirC Skew NumUp NumDn MinLoCord MaxHiCord MaxSubmerge Is_Ogee
27.811400,23.290000,2.6,0, 20, 20, , , 0.95, 0, 0,0,,
 9948.27 9954.71 9964.34 9967.06 9979.41 9981.38 9984.58 9984.58 9991.76 9998.43
10004.1110015.4210015.4210015.4710016.4610028.8110032.5110041.1610049.5510052.47
  106.84  106.86  106.97  106.96  107.07  107.08  107.08  107.08  107.08  107.17
  107.15  107.08  107.08  107.08  107.07  106.96  106.97  106.91  106.95  106.89
 -893.16 -893.14 -893.03 -893.04 -892.93 -892.92 -892.92  104.58  104.58  104.67
  104.65  104.58 -892.92 -892.92 -892.93 -893.04 -893.03 -893.09 -893.05 -893.11
 9948.27 9954.71 9964.34 9967.06 9979.41 9981.38 9984.58 9984.58 9991.76 9998.43
10004.1110015.4210015.4210015.4710016.4610028.8110032.5110041.1610049.5510052.47
  106.84  106.86  106.97  106.96  107.07  107.08  107.08  107.08  107.08  107.17
  107.15  107.08  107.08  107.08  107.07  106.96  106.97  106.91  106.95  106.89
 -893.16 -893.14 -893.03 -893.04 -892.93 -892.92 -892.92  104.58  104.58  104.67
  104.65  104.58 -892.92 -892.92 -892.93 -893.04 -893.03 -893.09 -893.05 -893.11
BR Coef=-1 , 0 , 0 ,, 0 ,,,0.8,0,1,0,
WSPro=,,,, 1 ,,,, 0 ,,,, 0 ,,,,-1 ,-1 ,-1 , 0 , 0 , 0 , 0 , 0
BC Design=,, 0 ,, 0 ,,,,,,

Type RM Length L Ch R = 1 ,11432.72,424.394600,424.394600,424.394600
XS GIS Cut Line= 4
900629.068043083798011.924080521 899938.38124609 797963.08764033
899875.591537267798028.202893928898357.010801792797844.484856993
#Sta/Elev= 30
9265.528116.3019 9500.18105.58459750.804103.26549770.854105.27599960.596106.2239
9977.217105.20979991.62399.0611910006.0396.5331110034.84104.073310169.87104.4025
 10230.3101.810110411.62106.5637 10713.8110.147310784.32108.769810804.46103.1993
10824.61101.961810844.75106.246710907.67108.993411026.07110.437311056.28107.6446
11106.65109.113911136.87113.015311287.96 111.81611298.03109.975411328.25113.7021
11388.69106.629211428.98111.9049 11459.2127.181311469.27130.023811578.05138.7407
#Mann= 3 , 0 , 0
9265.528    0.12       09265.528    0.12       011578.05    0.12       0
#XS Ineff= 2 , 0
       0                   10504       0
Bank Sta=9265.528,11578.05
Exp/Cntr=0.3,0.1

Type RM Length L Ch R = 1 ,11008.33,436.679400,436.679400,436.679400
XS GIS Cut Line= 2
900904.386059369 797930.12990613898640.357363456797444.665663341
#Sta/Elev= 30
8840.014 121.716 9013.25  109.989033.705106.72439115.524108.2669 9545.0798.73086
9708.707103.4998 9964.39102.46269974.617100.69569995.07290.7867110025.7594.71973
10056.4494.6641110066.66101.667910087.12102.098310179.16101.581510220.0796.95018
10393.9498.8147310434.8596.8124710496.2199.1298710526.8997.5609410547.35102.9883
10772.35105.604710823.48  97.17710895.07103.338510915.53101.132610956.44106.0063
10976.89 105.33810997.35110.703611068.94152.804911120.08168.181911155.51172.9953
#Mann= 3 , 0 , 0
8840.014    0.04       08840.014    0.04       011155.51    0.04       0
#XS Ineff= 2 , 0
       0                10122.45       0
Bank Sta=8840.014,11155.51
Exp/Cntr=0.3,0.1

Type RM Length L Ch R = 1 ,10571.65,347.071700,347.071700,347.071700
XS GIS Cut Line= 3
900776.400031725797634.438049159899929.044262494797351.986126082
898772.756702398797268.133211418
#Sta/Elev= 30
9277.587116.56139342.308111.00469532.045103.76969763.94598.01587 9816.6598.46765
9879.89690.637059911.51894.486169974.76495.667689995.84687.5305910016.9389.86817
10038.0188.6075210059.09 93.8212 10111.897.1348310335.2594.9153710585.91 95.9932
10636.0491.4623810676.1592.03667 10696.297.5936810716.2597.7090310756.3690.93629
10776.4190.5104210846.5995.8401911097.25100.980311137.35104.182411157.41113.0966
11197.51136.146311227.59148.784411257.67155.1526 11307.8181.7557 11330.1  190.08
#Mann= 3 , 0 , 0
9277.587   0.058       09277.587   0.058       0 11330.1   0.058       0
#XS Ineff= 2 , 0
       0                 10149.5       0
Bank Sta=9277.587,11330.1
Exp/Cntr=0.3,0.1

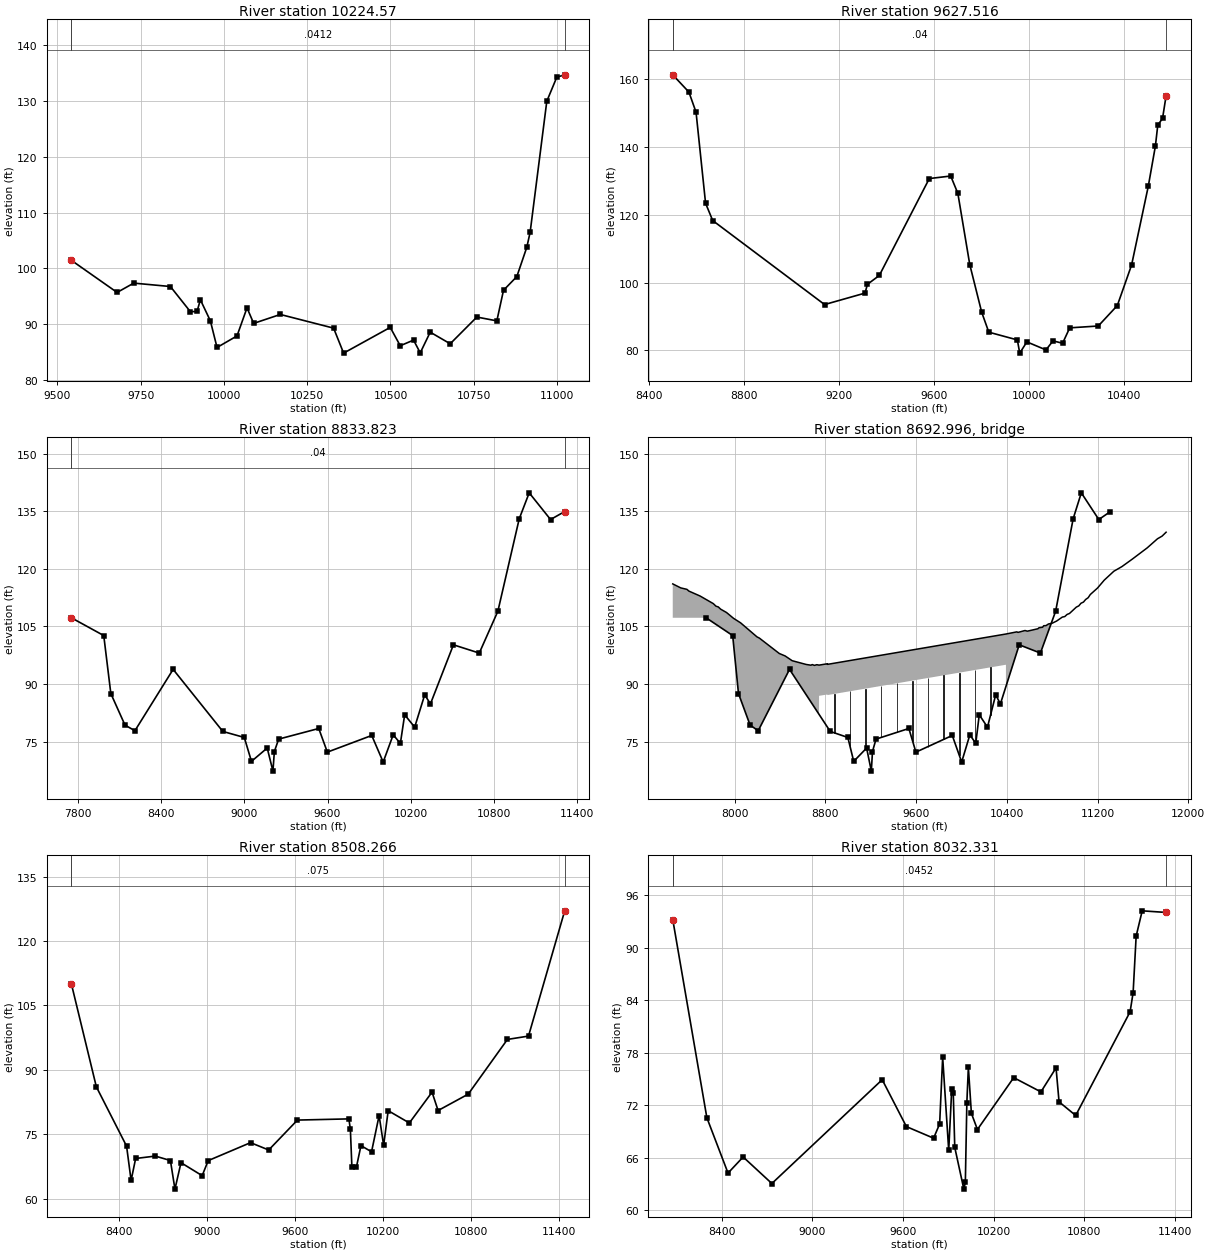
Type RM Length L Ch R = 1 ,10224.57,597.058100,597.058100,597.058100
XS GIS Cut Line= 2
900692.380105336797102.188916807 899211.29943877797078.596481411
#Sta/Elev= 30
9541.841101.41679679.23895.645789729.24497.319449839.25896.708579899.26692.18595
9919.26992.22835 9929.2794.331919959.27490.539279979.276 85.762210039.2887.83782
10069.2992.8776110089.2990.08834 10169.391.6893310329.3289.2335510359.3284.74633
10499.3489.3678510529.35 86.072810569.3587.0875510589.3584.7910110619.3688.51136
10679.3686.4270310759.3891.2256510819.3890.5397610839.3996.0337610879.3998.49397
10909.39103.7674 10919.4106.4769 10969.4 129.98410999.41134.304711023.11134.7233
#Mann= 3 , 0 , 0
9541.841  0.0412       09541.841  0.0412       011023.11  0.0412       0
#XS Ineff= 2 , 0
       0                10203.83       0
Bank Sta=9541.841,11023.11
Exp/Cntr=0.3,0.1

Type RM Length L Ch R = 1 ,9627.516,793.693100,793.693100,793.693100
XS GIS Cut Line= 2
901342.903611629796934.871536129899269.986944962796762.996536129
#Sta/Elev= 30
8498.879161.16168567.016156.08058597.119150.14868637.256123.33968667.359118.2439
9138.97293.505369309.55596.881329319.58999.458499369.761102.07899580.482130.6117
 9670.79131.35939700.893126.24719751.065105.29879801.23791.28062 9831.3485.37194
9951.751 83.08969961.78679.202159991.88982.5146710072.1680.1526410102.2782.81262
 10142.482.1104210172.5186.6463710292.9287.1897910373.1993.21941 10433.4105.1649
10503.64128.307310533.74140.186810543.78146.367710563.84148.312810578.91155.0295
#Mann= 3 , 0 , 0
8498.879    0.04       08498.879    0.04       010578.91    0.04       0
#XS Ineff= 2 , 0
       09629.324                       0
Bank Sta=8498.879,10578.91
Exp/Cntr=0.3,0.1

Type RM Length L Ch R = 1 ,8833.823,325.556800,325.556800,325.556800
XS GIS Cut Line= 5
902243.945278295795559.871536129901254.361944962795773.413202796
899738.736944962796174.454869463899306.445278295796294.246536129
898785.611944962796419.246536129
#Sta/Elev= 30
7749.102107.26597983.317102.63638034.46887.53567 8136.7779.319528208.38177.85072
8484.53893.830758843.55777.669748998.719 76.0994 9050.4469.877069164.22673.35069
9205.60267.334259215.94672.443119246.97975.671539536.61578.43787 9598.68  72.281
9919.34976.62138 10002.169.7009510074.5176.8021310126.2374.5409110157.2682.00509
10229.6778.7840310302.0887.20716 10343.584.8388410509.53100.227910696.3298.07429
10830.74108.9809   10985133.047511056.99139.803611211.25132.849911313.46134.9321
#Mann= 3 , 0 , 0
7749.102    0.04       07749.102    0.04       011313.46    0.04       0
#XS Ineff= 2 , 0
       09619.112                       0
Bank Sta=7749.102,11313.46
Exp/Cntr=0.3,0.1

Type RM Length L Ch R = 3 ,8692.996,,,
BEGIN DESCRIPTION:
END DESCRIPTION:
Bridge Culvert--1,0,-1,-1, 0
Deck Dist Width WeirC Skew NumUp NumDn MinLoCord MaxHiCord MaxSubmerge Is_Ogee
105.053400,115.450000,2.6,0, 60, 60, , , 0.95, 0, 0,0,,
 7455.01 7525.42 7579.75 7597.86 7696.26 7812.78 7835.88 7856.58 7877.28 7929.02
 7991.12 8053.21 8197.85 8218.51 8394.08 8445.72 8507.68 8631.61 8672.92 8685.10
 8703.91 8725.12 8744.80 8744.80 8817.50 8819.4710392.4110392.4110488.4410498.74
10560.5810581.1910673.9810684.4310715.2210725.4810746.1510766.7710797.7110838.95
10889.7210911.1210931.7410952.3611012.8911034.8511053.9511076.0911095.0011117.33
11136.0611199.8211259.2411343.9211414.7811505.8811637.4711728.5711769.0611804.54
  116.09  115.05  114.67  114.21  112.93  110.95  110.29  110.09  109.51  108.64
  107.12  105.95  102.29  101.98   97.97   97.33   96.09   95.11   94.92   95.08
   94.87   95.05   94.94   94.94   95.29   95.14  103.04  103.04  103.60  103.46
  103.95  103.78  104.41  104.68  104.80  105.20  105.23  105.65  105.82  106.41
  107.45  107.58  108.14  108.38  110.04  110.37  111.05  111.36  112.03  112.49
  113.32  115.01  117.07  119.39  120.59  122.53  125.46  127.84  128.53  129.55
 -883.91 -884.95 -885.33 -885.79 -887.07 -889.05 -889.71 -889.91 -890.49 -891.36
 -892.88 -894.05 -897.71 -898.02 -902.03 -902.67 -903.91 -904.89 -905.08 -904.92
 -905.13 -904.95 -905.06   86.94   87.29   87.14   95.04 -896.96 -896.40 -896.54
 -896.05 -896.22 -895.59 -895.32 -895.20 -894.80 -894.77 -894.35 -894.18 -893.59
 -892.55 -892.42 -891.86 -891.62 -889.96 -889.63 -888.95 -888.64 -887.97 -887.51
 -886.68 -884.99 -882.93 -880.61 -879.41 -877.47 -874.54 -872.16 -871.47 -870.45
 7455.01 7525.42 7579.75 7597.86 7696.26 7753.09 7773.94 7812.78 7835.88 7856.58
 7877.28 7929.02 7991.12 8053.21 8177.20 8197.85 8218.51 8394.08 8445.72 8507.68
 8631.61 8672.92 8685.10 8703.91 8849.59 8849.5910488.4410498.7410521.3710521.37
10622.4310643.3710715.2210725.4810746.1510766.7710787.4010838.9510848.6610869.88
10890.5010911.1210931.7410952.3610972.9811034.8511053.9511076.0911095.0011117.33
11136.0611158.5711259.2411343.9211414.7811505.8811637.4711728.5711769.0611804.54
  116.09  115.05  114.67  114.21  112.93  111.83  111.67  110.95  110.29  110.09
  109.51  108.64  107.12  105.95  102.95  102.29  101.98   97.97   97.33   96.09
   95.11   94.92   95.08   94.87   95.30   95.30  103.60  103.46  103.76  103.76
  103.99  104.33  104.80  105.20  105.23  105.65  105.71  106.41  106.80  107.00
  107.46  107.58  108.14  108.38  109.08  110.37  111.05  111.36  112.03  112.49
  113.32  113.78  117.07  119.39  120.59  122.53  125.46  127.84  128.53  129.55
 -883.91 -884.95 -885.33 -885.79 -887.07 -888.17 -888.33 -889.05 -889.71 -889.91
 -890.49 -891.36 -892.88 -894.05 -897.05 -897.71 -898.02 -902.03 -902.67 -903.91
 -904.89 -905.08 -904.92 -905.13 -904.70   87.30   95.60   95.46   95.76 -896.24
 -896.01 -895.67 -895.20 -894.80 -894.77 -894.35 -894.29 -893.59 -893.20 -893.00
 -892.54 -892.42 -891.86 -891.62 -890.92 -889.63 -888.95 -888.64 -887.97 -887.51
 -886.68 -886.22 -882.93 -880.61 -879.41 -877.47 -874.54 -872.16 -871.47 -870.45
Pier Skew, UpSta & Num, DnSta & Num=  ,8880.43, 2 ,8987.24, 2 , 0 , 0 , 0 ,,
    4.00    4.00
 -904.55   95.45
    4.00    4.00
 -904.01   95.99
Pier Skew, UpSta & Num, DnSta & Num=  ,9018.07, 2 ,9126.88, 2 , 0 , 0 , 0 ,,
    4.00    4.00
 -903.86   96.14
    4.00    4.00
 -903.31   96.69
Pier Skew, UpSta & Num, DnSta & Num=  ,9155.70, 2 ,9266.53, 2 , 0 , 0 , 0 ,,
    4.00    4.00
 -903.17   96.83
    4.00    4.00
 -902.61   97.39
Pier Skew, UpSta & Num, DnSta & Num=  ,9293.34, 2 ,9406.18, 2 , 0 , 0 , 0 ,,
    4.00    4.00
 -902.48   97.52
    4.00    4.00
 -901.91   98.09
Pier Skew, UpSta & Num, DnSta & Num=  ,9430.97, 2 ,9545.83, 2 , 0 , 0 , 0 ,,
    4.00    4.00
 -901.79   98.21
    4.00    4.00
 -901.21   98.79
Pier Skew, UpSta & Num, DnSta & Num=  ,9568.60, 2 ,9685.48, 2 , 0 , 0 , 0 ,,
    4.00    4.00
 -901.10   98.90
    4.00    4.00
 -900.51   99.49
Pier Skew, UpSta & Num, DnSta & Num=  ,9706.24, 2 ,9825.13, 2 , 0 , 0 , 0 ,,
    4.00    4.00
 -900.41   99.59
    4.00    4.00
 -899.81  100.19
Pier Skew, UpSta & Num, DnSta & Num=  ,9843.87, 2 ,9964.78, 2 , 0 , 0 , 0 ,,
    4.00    4.00
 -899.71  100.29
    4.00    4.00
 -899.11  100.89
Pier Skew, UpSta & Num, DnSta & Num=  ,9981.51, 2 ,10104.42, 2 , 0 , 0 , 0 ,,
    4.00    4.00
 -899.02  100.98
    4.00    4.00
 -898.41  101.59
Pier Skew, UpSta & Num, DnSta & Num=  ,10119.14, 2 ,10244.07, 2 , 0 , 0 , 0 ,,
    4.00    4.00
 -898.33  101.67
    4.00    4.00
 -897.71  102.29
Pier Skew, UpSta & Num, DnSta & Num=  ,10256.77, 2 ,10383.72, 2 , 0 , 0 , 0 ,,
    4.00    4.00
 -897.64  102.36
    4.00    4.00
 -897.01  102.99
BR Coef=-1 , 0 , 0 ,, 0 ,,,0.8,0,1,0,
WSPro=,,,, 1 ,,,, 0 ,,,, 0 ,,,,-1 ,-1 ,-1 , 0 , 0 , 0 , 0 , 0
BC Design=,, 0 ,, 0 ,,,,,,

Type RM Length L Ch R = 1 ,8508.266,475.935100,475.935100,475.935100
XS GIS Cut Line= 4
902030.403611629795309.871536129901197.070278295795523.413202796
899582.486944962795940.079869463898764.778611629796137.996536129
#Sta/Elev= 30
8072.674110.05768243.42286.034138449.88472.215928480.85364.217158511.82369.33593
8646.02369.893338749.25468.860288780.22362.196778821.51668.357388966.05465.33249
9007.36468.840079296.53773.025869420.46971.312649616.69478.283289967.83378.56035
 9978.1676.150439988.48867.4082210019.47 67.336610050.4572.3371310122.7570.89133
10174.3979.3329210205.3772.4110710236.3580.4742210380.9477.6110710535.8584.78822
10577.1680.5081710783.0284.3278811050.53 97.071411194.5797.8482211441.73127.0298
#Mann= 3 , 0 , 0
8072.674   0.075       08072.674   0.075       011441.73   0.075       0
#XS Ineff= 2 , 0
       0 9693.04                       0
Bank Sta=8072.674,11441.73
Exp/Cntr=0.3,0.1

Type RM Length L Ch R = 1 ,8032.331,507.739700,507.739700,507.739700
XS GIS Cut Line= 3
901920.685825393 795288.02309244899858.295548713795353.844058717
898656.796936504795392.189759107
#Sta/Elev= 30
8076.21293.205718302.01370.577448442.08464.256068542.13566.095018732.23263.06533
9462.60374.917659622.68569.562789802.77768.240089842.797 69.87169862.80777.47516
9902.827 66.84629922.83873.854319932.84373.435369942.84867.1891410002.8862.42434
10012.8863.2008710022.8972.3109310032.8976.33369 10052.971.0754710092.9269.23195
10333.05 75.154410513.1473.5258910613.19 76.2665 10633.272.3914310743.2670.83377
11103.4482.6726111123.4584.8695311143.46 91.311311183.48 94.197711341.7694.01333
#Mann= 3 , 0 , 0
8076.212  0.0452       08076.212  0.0452       011341.76  0.0452       0
#XS Ineff= 2 , 0
       09502.525        10041.99       0
Bank Sta=8076.212,11341.76
Exp/Cntr=0.3,0.1

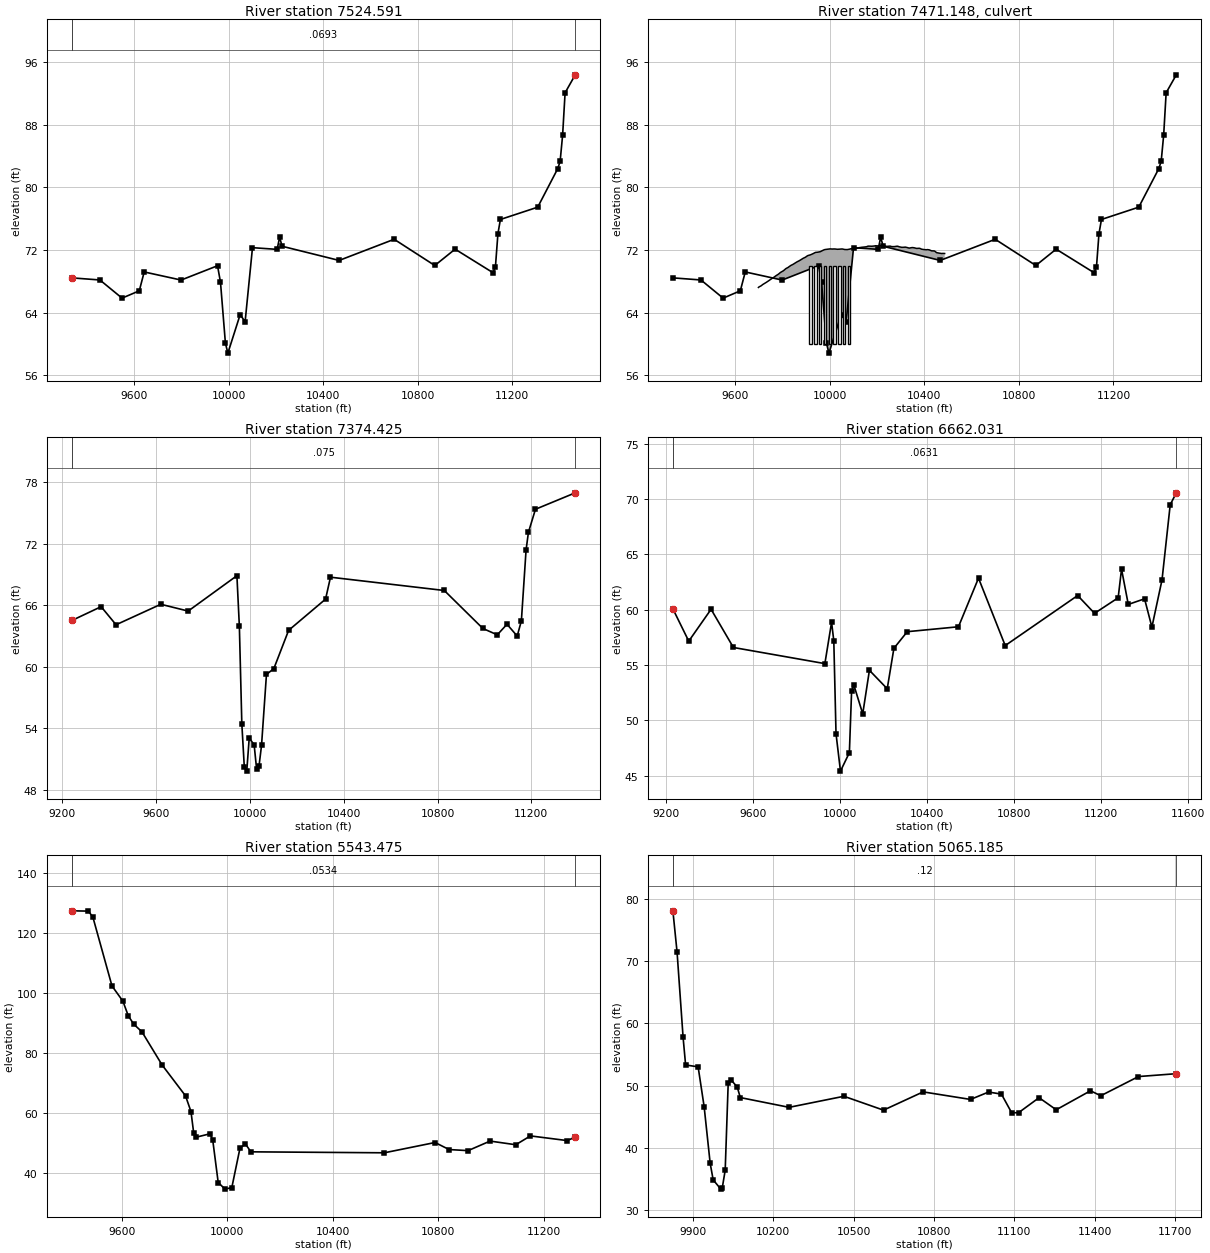
Type RM Length L Ch R = 1 ,7524.591,150.166600,150.166600,150.166600
XS GIS Cut Line= 6
900769.070232091794977.309695371900279.614752868 794835.04271917
899952.345924499794930.616801791899546.039830441795060.059451225
899125.351219778795225.458392169898744.214529776795351.305412453
#Sta/Elev= 30
9335.67968.436619454.47168.167819548.19565.847319621.09266.78131 9641.9269.19302
9798.12868.157549952.25769.984679964.79467.883549985.62960.087989996.04758.81878
10048.1463.7527210068.9762.8144210100.2272.2963710204.5472.0776710215.0373.62361
10225.5372.4760410466.9270.6654110699.8473.3687110871.7670.0186610957.7272.10594
11117.82 69.103111128.3569.8226411138.88 74.064511149.4175.8997711307.3877.47195
11391.6282.3674611402.1683.3104511412.6986.6553611423.2292.0905511466.1794.38466
#Mann= 3 , 0 , 0
9335.679  0.0693       09335.679  0.0693       011466.17  0.0693       0
#XS Ineff= 2 , 0
       09609.908         10161.4       0
Bank Sta=9335.679,11466.17
Exp/Cntr=0.3,0.1

Type RM Length L Ch R = 2 ,7471.148,,,
Bridge Culvert--1,0,-1,-1, 0
Deck Dist Width WeirC Skew NumUp NumDn MinLoCord MaxHiCord MaxSubmerge Is_Ogee
53.083,44,2.6,0,103,103, , , 0.95, 0, 0,0,,
 9697.66 9699.73 9710.11 9715.10 9720.49 9730.87 9741.25 9751.63 9752.40 9762.01
 9772.39 9782.77 9789.71 9793.15 9803.53 9813.91 9824.29 9827.01 9834.67 9845.05
 9855.43 9864.31 9865.81 9876.19 9886.57 9896.95 9901.62 9907.33 9917.71 9928.09
 9938.40 9938.47 9938.92 9948.85 9959.23 9969.61 9976.15 9979.99 9990.3710000.75
10011.1410013.3810021.5210031.9010042.2810050.6110052.6610063.0410073.4210083.81
10087.8410094.1910104.5710114.9510125.0710125.3310135.7110146.1010156.1510156.48
10161.3410167.0310177.5810188.1310192.7810198.6710209.2210219.7710224.2210230.32
10240.8610251.4110255.6610261.9610272.5110283.0510287.1010293.6010304.1510314.70
10318.5410325.2510335.7910346.3410349.9810356.8910367.4410377.9810381.4210388.53
10399.0810409.6310412.8710420.1810430.7210441.2710444.3110451.8210462.3710472.91
10475.7510483.4610485.87
   67.21   67.27   67.44   67.57   67.67   67.86   68.07   68.29   68.31   68.49
   68.72   68.92   69.10   69.17   69.35   69.62   69.79   69.86   70.02   70.18
   70.38   70.54   70.55   70.73   70.93   71.08   71.19   71.29   71.38   71.52
   71.68   71.68   71.69   71.72   71.78   71.94   72.03   72.06   72.10   72.14
   72.12   72.13   72.13   72.09   72.11   72.13   72.13   72.06   72.05   72.11
   72.15   72.17   72.22   72.21   72.30   72.30   72.35   72.38   72.42   72.43
   72.49   72.49   72.48   72.51   72.54   72.53   72.51   72.60   72.60   72.54
   72.46   72.49   72.49   72.43   72.43   72.48   72.48   72.41   72.34   72.35
   72.37   72.33   72.24   72.30   72.31   72.28   72.20   72.22   72.20   72.10
   72.05   72.03   72.05   72.02   71.89   71.88   71.84   71.66   71.60   71.55
   71.56   71.56   71.55
                                                                                
                                                                                
                                                                                
                                                                                
                                                                                
                                                                                
                                                                                
                                                                                
                                                                                
                                                                                
                        
 9697.66 9699.73 9710.11 9715.10 9720.49 9730.87 9741.25 9751.63 9752.40 9762.01
 9772.39 9782.77 9789.71 9793.15 9803.53 9813.91 9824.29 9827.01 9834.67 9845.05
 9855.43 9864.31 9865.81 9876.19 9886.57 9896.95 9901.62 9907.33 9917.71 9928.09
 9938.40 9938.47 9938.92 9948.85 9959.23 9969.61 9976.15 9979.99 9990.3710000.75
10011.1410013.3810021.5210031.9010042.2810050.6110052.6610063.0410073.4210083.81
10087.8410094.1910104.5710114.9510125.0710125.3310135.7110146.1010156.1510156.48
10161.3410167.0310177.5810188.1310192.7810198.6710209.2210219.7710224.2210230.32
10240.8610251.4110255.6610261.9610272.5110283.0510287.1010293.6010304.1510314.70
10318.5410325.2510335.7910346.3410349.9810356.8910367.4410377.9810381.4210388.53
10399.0810409.6310412.8710420.1810430.7210441.2710444.3110451.8210462.3710472.91
10475.7510483.4610485.87
   67.21   67.27   67.44   67.57   67.67   67.86   68.07   68.29   68.31   68.49
   68.72   68.92   69.10   69.17   69.35   69.62   69.79   69.86   70.02   70.18
   70.38   70.54   70.55   70.73   70.93   71.08   71.19   71.29   71.38   71.52
   71.68   71.68   71.69   71.72   71.78   71.94   72.03   72.06   72.10   72.14
   72.12   72.13   72.13   72.09   72.11   72.13   72.13   72.06   72.05   72.11
   72.15   72.17   72.22   72.21   72.30   72.30   72.35   72.38   72.42   72.43
   72.49   72.49   72.48   72.51   72.54   72.53   72.51   72.60   72.60   72.54
   72.46   72.49   72.49   72.43   72.43   72.48   72.48   72.41   72.34   72.35
   72.37   72.33   72.24   72.30   72.31   72.28   72.20   72.22   72.20   72.10
   72.05   72.03   72.05   72.02   71.89   71.88   71.84   71.66   71.60   71.55
   71.56   71.56   71.55
                                                                                
                                                                                
                                                                                
                                                                                
                                                                                
                                                                                
                                                                                
                                                                                
                                                                                
                                                                                
                        
BR Coef=-1 , 0 , 0 ,, 0 ,,,0.8,-1,,0,
WSPro=,,,, 1 ,,,, 0 ,,,, 0 ,,,,-1 ,-1 ,-1 , 0 , 0 , 0 , 0 , 0
Multiple Barrel Culv=2,10,10.17,44,0.013,0.7,1,8,3,60,52,9,Culvert #1, 0, 53.083
 9918.64 9918.64 9938.98 9938.98 9959.32 9959.32 9979.66 9979.6610000.0010000.00
10020.3410020.3410040.6810040.6810061.0210061.0210081.3610081.36
Culvert Bottom n=0.013
BC Design=,, 0 ,, 0 ,,,,,,

Type RM Length L Ch R = 1 ,7374.425,712.393300,712.393300,712.393300
XS GIS Cut Line= 6
900782.748367108794835.968966872900317.437757666794670.892067502
900168.083673557794711.283423582899643.121817517794880.277993677
898959.952278834795045.676934621898715.449496569795056.463822074
#Sta/Elev= 30
9239.93364.521969364.87165.869919428.53564.105539619.52766.103479736.183 65.4405
9944.14468.889579954.64963.939859965.15454.44039 9975.6650.247629986.16549.83553
9996.67153.0598210017.6852.4075610028.1950.0291510038.6950.37525 10049.252.34462
10070.2159.2594110101.7259.8302310164.7663.5619110322.34 66.605610343.3568.74384
10828.9267.4473410993.5463.74247 11054.9 63.125711096.4364.15598 11139.963.00326
11157.7464.4905711177.7671.3954911187.7773.11441 11217.875.3676211387.52 76.9697
#Mann= 3 , 0 , 0
9239.933   0.075       09239.933   0.075       011387.52   0.075       0
#XS Ineff= 2 , 0
       09529.639         10166.5       0
Bank Sta=9239.933,11387.52
Exp/Cntr=0.3,0.1

Type RM Length L Ch R = 1 ,6662.031,1118.556300,1118.556300,1118.556300
XS GIS Cut Line= 4
900816.119833408794196.468547956900106.629775548 794038.14402516
899227.855688284794224.416915995898703.671844672794667.271968341
#Sta/Elev= 30
 9233.9160.067039306.77957.153199409.23960.033249511.69956.581929931.78355.12421
9962.51758.853639972.73957.191119982.961 48.789410003.4145.4139410044.2947.08367
10054.5252.6527310064.7453.1960410105.6350.5900210136.2954.5184410218.0752.85387
10248.7456.5066810310.0758.0082510545.1858.4525210637.1862.8435510759.85 56.7537
11092.4861.2744511169.9659.6661711278.4261.0692611293.9263.6550411324.9160.47031
11399.6260.9775111433.3858.4220611479.8662.6915411517.4469.4727111545.3670.54971
#Mann= 3 , 0 , 0
 9233.91  0.0631       0 9233.91  0.0631       011545.36  0.0631       0
#XS Ineff= 2 , 0
       09531.263        10632.77       0
Bank Sta=9233.91,11545.36
Exp/Cntr=0.3,0.1

Type RM Length L Ch R = 1 ,5543.475,478.289700,478.289700,478.289700
XS GIS Cut Line= 3
900242.430881054792969.139600643898991.706473287793293.401484138
898562.331116173793737.158787251
#Sta/Elev= 30
9410.361 127.3159473.559 127.2199490.352125.16699562.666102.29169603.98997.23899
 9624.6592.318399645.31189.556999676.30387.015189752.48676.011969841.59365.69292
9862.25460.470669872.58453.337989882.91551.944719934.56853.059629944.89950.93422
 9965.5636.833479991.56634.6277410017.2135.14423 10048.248.2840310068.8749.67836
10089.5347.0503910595.7346.7265610788.1550.1544310841.5147.8064410913.4147.44881
10996.8750.6311711094.2849.4098211149.9452.3538311289.0850.7994211319.9251.93048
#Mann= 3 , 0 , 0
9410.361  0.0534       09410.361  0.0534       011319.92  0.0534       0
#XS Ineff= 2 , 0
       0                10714.67       0
Bank Sta=9410.361,11319.92
Exp/Cntr=0.3,0.1

Type RM Length L Ch R = 1 ,5065.185,106.424700,106.424700,106.424700
XS GIS Cut Line= 5
899396.652076751792641.075724974899285.540965617 792858.08961387
899261.235410094792898.020169422898669.807568133793219.080997929
898096.955896169793935.346558332
#Sta/Elev= 30
 9824.87 78.11919840.513  71.4599862.98257.75964 9872.3853.308679919.15553.00962
9941.62446.593689964.09337.502039975.32734.8188910004.03 33.325310009.0333.45669
10020.2736.35326 10031.550.3620610042.7350.88029 10065.2 49.765510076.7648.06039
10259.0646.4905410463.8748.2701410611.7946.0373110759.7148.9763910936.8147.76161
11004.2148.9519511052.2448.6192511090.4745.6201111116.0845.62066 11192.948.04412
11256.9346.0973711384.9849.1552911423.3948.3557411564.2451.4445611705.5451.90569
#Mann= 3 , 0 , 0
 9824.87    0.12       0 9824.87    0.12       011705.54    0.12       0
#XS Ineff= 2 , 0
       0                10453.29       0
Bank Sta=9824.87,11705.54
Exp/Cntr=0.3,0.1