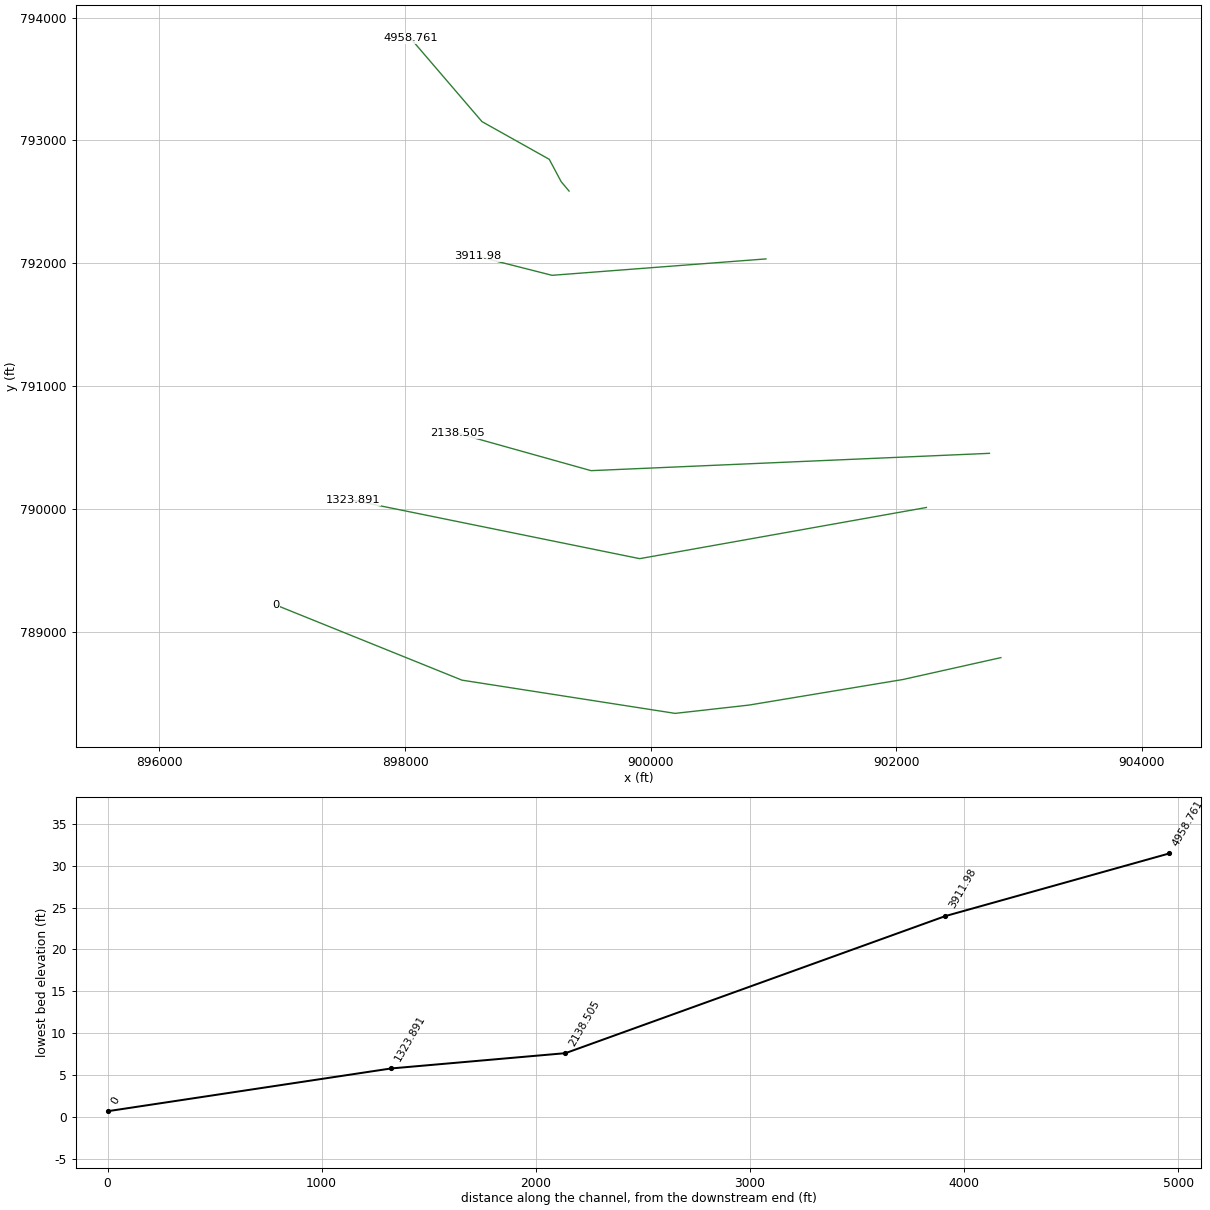
HEC-RAS study 11954_ras.prj: 11954

--- 11954_ras.g01 (geometry) --- (continued)

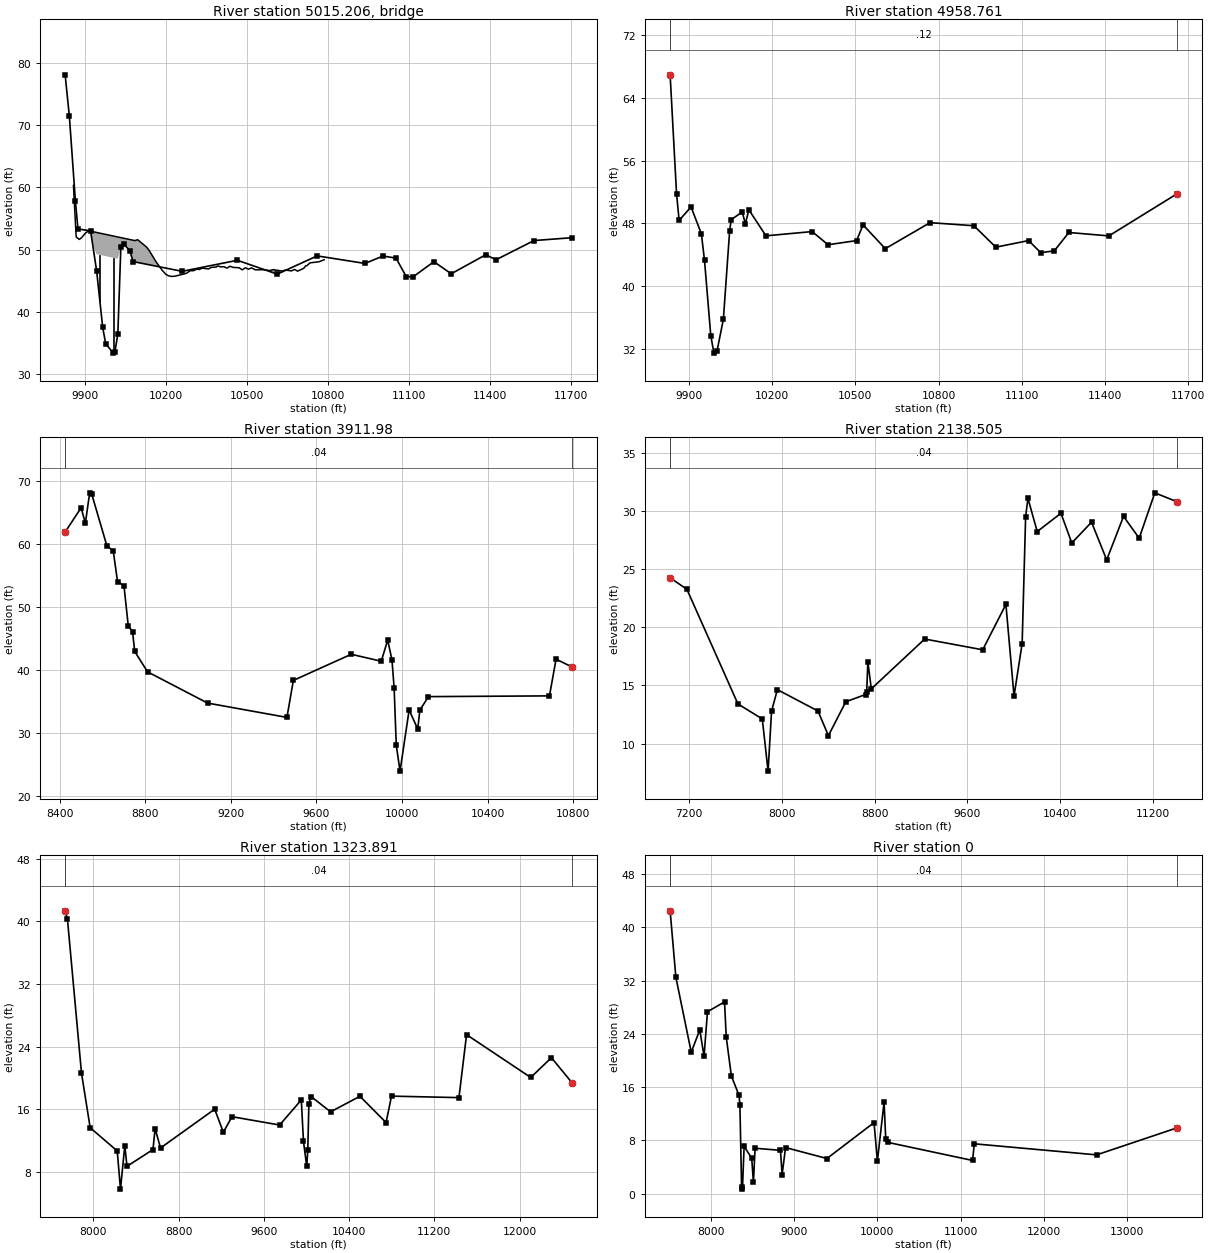
Type RM Length L Ch R = 3 ,5015.206,,,
BEGIN DESCRIPTION:
END DESCRIPTION:
Bridge Culvert--1,0,-1,-1, 0
Deck Dist Width WeirC Skew NumUp NumDn MinLoCord MaxHiCord MaxSubmerge Is_Ogee
31.067350,44.290000,2.6,0, 60, 60, , , 0.95, 0, 0,0,,
 9855.72 9865.26 9866.12 9877.51 9886.17 9900.28 9904.34 9904.34 9911.66 9923.05
 9927.2510054.9310054.9310083.8710093.8510116.6610127.8510137.1410162.1810185.08
10198.8110207.9710219.3710230.8610265.1910276.6010288.0110302.0010310.8210322.23
10333.6410356.4610367.8710385.0810390.6910402.1010413.5110424.9210436.3310447.40
10470.5510481.9610493.3710504.7810516.1910530.4910561.8310584.6410596.0510630.28
10641.6910664.5110675.9210687.3310710.1510717.4310721.5510732.9610767.1910785.88
   60.32   52.43   52.00   51.63   51.92   52.65   52.77   52.77   52.98   53.12
   52.88   51.70   51.70   51.44   51.58   50.77   50.35   49.81   48.02   46.65
   46.00   45.78   45.67   45.70   46.06   46.22   46.58   46.60   46.82   46.79
   47.00   46.88   47.13   47.18   47.37   47.21   47.24   47.01   47.31   47.13
   47.06   46.73   47.07   46.83   47.05   46.73   46.75   46.61   46.77   46.53
   46.70   46.56   46.80   46.52   46.98   47.38   47.40   47.85   48.04   48.36
 -939.68 -947.57 -948.00 -948.37 -948.08 -947.35 -947.23   49.27   49.48   49.62
   49.38   48.20 -948.30 -948.56 -948.42 -949.23 -949.65 -950.19 -951.98 -953.35
 -954.00 -954.22 -954.33 -954.30 -953.94 -953.78 -953.42 -953.40 -953.18 -953.21
 -953.00 -953.12 -952.87 -952.82 -952.63 -952.79 -952.76 -952.99 -952.69 -952.87
 -952.94 -953.27 -952.93 -953.17 -952.95 -953.27 -953.25 -953.39 -953.23 -953.47
 -953.30 -953.44 -953.20 -953.48 -953.02 -952.62 -952.60 -952.15 -951.96 -951.64
 9855.72 9865.26 9866.12 9877.51 9886.17 9900.28 9911.66 9923.74 9923.74 9927.25
10074.3310074.3310083.8710093.8510127.8510139.2910162.1810185.0810198.8110207.97
10219.3710230.8610265.1910276.6010288.0110302.0010310.8210322.2310333.6410356.46
10367.8710385.0810390.6910402.1010413.5110424.9210436.3310447.4010468.1710470.55
10481.9610493.3710504.7810516.1910530.4910561.8310584.6410596.0510630.2810634.35
10641.6910664.5110675.9210687.3310710.1510717.4310721.5510732.9610767.1910785.88
   60.32   52.43   52.00   51.63   51.92   52.65   52.98   53.08   53.08   52.88
   51.52   51.52   51.44   51.58   50.35   49.67   48.02   46.65   46.00   45.78
   45.67   45.70   46.06   46.22   46.58   46.60   46.82   46.79   47.00   46.88
   47.13   47.18   47.37   47.21   47.24   47.01   47.31   47.13   47.01   47.06
   46.73   47.07   46.83   47.05   46.73   46.75   46.61   46.77   46.53   46.65
   46.70   46.56   46.80   46.52   46.98   47.38   47.40   47.85   48.04   48.36
 -939.68 -947.57 -948.00 -948.37 -948.08 -947.35 -947.02 -946.92   49.58   49.38
   48.02 -948.48 -948.56 -948.42 -949.65 -950.33 -951.98 -953.35 -954.00 -954.22
 -954.33 -954.30 -953.94 -953.78 -953.42 -953.40 -953.18 -953.21 -953.00 -953.12
 -952.87 -952.82 -952.63 -952.79 -952.76 -952.99 -952.69 -952.87 -952.99 -952.94
 -953.27 -952.93 -953.17 -952.95 -953.27 -953.25 -953.39 -953.23 -953.47 -953.35
 -953.30 -953.44 -953.20 -953.48 -953.02 -952.62 -952.60 -952.15 -951.96 -951.64
Pier Skew, UpSta & Num, DnSta & Num=  ,9953.87, 2 ,9973.27, 2 , 0 , 0 , 0 ,,
    4.00    4.00
 -947.37   52.63
    4.00    4.00
 -947.54   52.46
Pier Skew, UpSta & Num, DnSta & Num=  ,10005.40, 2 ,10024.80, 2 , 0 , 0 , 0 ,,
    4.00    4.00
 -947.84   52.16
    4.00    4.00
 -948.02   51.98
BR Coef=-1 , 0 , 0 ,, 0 ,,,0.8,0,1,0,
WSPro=,,,, 1 ,,,, 0 ,,,, 0 ,,,,-1 ,-1 ,-1 , 0 , 0 , 0 , 0 , 0
BC Design=,, 0 ,, 0 ,,,,,,

Type RM Length L Ch R = 1 ,4958.761,1046.781000,1046.781000,1046.781000
XS GIS Cut Line= 5
899335.888187855792587.256280541899271.652076751792663.645169422
899174.429854512792845.936836094898626.451271832793153.008425757
898044.872562855793831.179891661
#Sta/Elev= 30
9832.07266.946839855.25651.794079864.52748.380669907.51850.102139944.74946.67791
9956.08243.287289978.74933.657749990.08231.4622810001.4231.7815510024.0835.77602
10046.7547.0867110052.2748.4892110092.0849.4491710103.42 47.958210116.02 49.7396
10177.4746.4186510344.1646.9609210401.4745.2821710504.7745.8119610527.5747.82286
10607.8144.7826610769.2548.0962610927.3347.7068511006.3844.9729711124.94 45.8135
11168.2644.2692311217.1544.5010111269.8546.8438311414.0446.4087111660.02 51.7838
#Mann= 3 , 0 , 0
9832.072    0.12       09832.072    0.12       011660.02    0.12       0
#XS Ineff= 2 , 0
       0                10361.27       0
Bank Sta=9832.072,11660.02
Exp/Cntr=0.3,0.1

Type RM Length L Ch R = 1 , 3911.98,1773.474300,1773.474300,1773.474300
XS GIS Cut Line= 3
900939.385418413792034.781326397899197.133590839791901.173057411
898592.273511942792054.901550514
#Sta/Elev= 30
8424.34661.86551 8498.9565.704288519.00963.275728539.06868.079028549.09767.83884
8619.30259.71461 8649.3958.858818669.44954.016058699.53753.348028719.59647.00101
8739.65546.078758749.68442.95327 8809.8639.712549090.68234.762739461.769 32.4923
9491.85738.35699 9762.6542.494689903.06141.392619933.14944.748329953.20741.58826
9963.23737.163799973.26628.073049990.88123.9790110033.4433.6804510073.5630.64773
10083.5933.6336610123.7135.7846510689.8135.9033710720.7641.72251 10795.840.47141
#Mann= 3 , 0 , 0
8424.346    0.04       08424.346    0.04       0 10795.8    0.04       0
#XS Ineff= 2 , 0
       09766.691        10106.21       0
Bank Sta=8424.346,10795.8
Exp/Cntr=0.3,0.1

Type RM Length L Ch R = 1 ,2138.505,814.613800,814.613800,814.613800
XS GIS Cut Line= 3
902759.411313603790451.260973766899515.053674714790310.201945988
 898429.98423027790614.021390432
#Sta/Elev= 30
7034.71424.238697179.26223.250097619.67813.401177829.87612.106637879.9237.626367
7909.95212.774377959.99914.62845 8310.3312.791038400.41510.675128550.55613.58517
8720.71714.208328730.72714.413388740.73617.004728770.76414.695659231.19918.97706
9731.67118.04985 9931.8621.9500610001.9314.0745210071.9918.5913210102.0229.49146
10122.0431.0586110202.1228.2100810406.8129.7832610500.2727.2274110670.8129.01393
10801.4225.7767110946.8129.5124911081.8127.6384611216.8131.5364411408.9430.76762
#Mann= 3 , 0 , 0
7034.714    0.04       07034.714    0.04       011408.94    0.04       0
#XS Ineff= 2 , 0
       09934.044        10285.96       0
Bank Sta=7034.714,11408.94
Exp/Cntr=0.3,0.1

Type RM Length L Ch R = 1 ,1323.891,1323.891500,1323.891500,1323.891500
XS GIS Cut Line= 3
902246.075770416790010.223050933899911.006325972789593.556384267
897574.637628546790069.300495739
#Sta/Elev= 30
7735.97641.360237757.38540.328357889.43820.620597970.70213.648818224.65110.67785
8255.125 5.800038295.75611.368878316.0728.7117078559.86310.859718580.17913.53172
8630.96911.057839138.86716.01515 9220.1313.071229301.39415.054969748.34413.99149
9951.50317.196069971.81911.9390610002.298.69280710012.4510.7967510022.6116.71567
10042.92 17.634910226.3215.6776410501.8617.6641410746.7814.3082910797.8117.68328
11430.5317.4922411501.9725.5368712104.0720.0660912297.9722.5959412492.2419.37986
#Mann= 3 , 0 , 0
7735.976    0.04       07735.976    0.04       012492.24    0.04       0
#XS Ineff= 2 , 0
       09627.694        10178.63       0
Bank Sta=7735.976,12492.24
Exp/Cntr=0.3,0.1

Type RM Length L Ch R = 1 ,       0,0.000000,0.000000,0.000000
XS GIS Cut Line= 6
902852.329852773788787.353547289902055.856959735788609.412006797
900800.143104144 788400.77164858900199.606376164788333.404794548
898463.526517435788604.022717962896949.637628546789215.133829073
#Sta/Elev= 30
7513.08842.487517582.078 32.50897766.51521.255297868.98124.609327920.21320.63254
7961.19927.341028165.97628.812038186.623 23.51578248.10217.685548340.19914.76223
8350.33313.396118370.6011.0713068380.7350.6965948401.003 7.122968492.2115.333528
8512.4791.7006828532.7476.8355188836.9546.5231978857.2412.8817488897.8146.939928
9394.6835.2923459959.90510.687049999.9934.90753410080.2513.7515910100.368.231559
10130.537.70223511142.445.00080411162.687.50162412630.735.84081813596.299.901098
#Mann= 3 , 0 , 0
7513.088    0.04       07513.088    0.04       013596.29    0.04       0
#XS Ineff= 2 , 0
       09366.056        10187.92       0
Bank Sta=7513.088,13596.29
Exp/Cntr=0.3,0.1